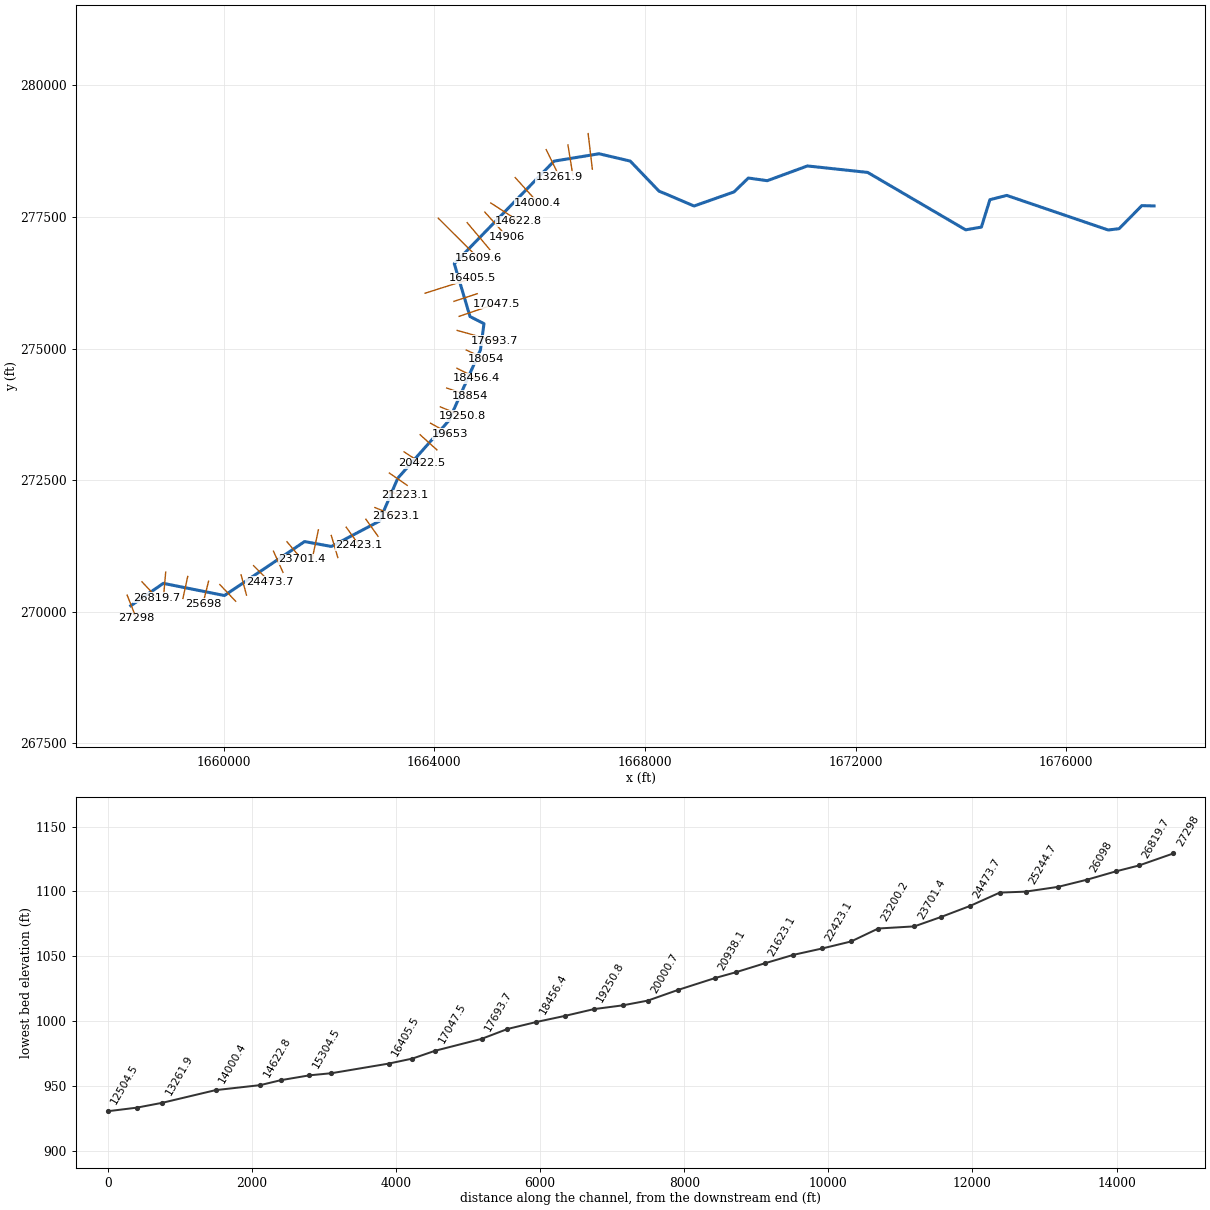
--- PINECRK.prj (project) ---

Proj Title=PINECRK
Current Plan=p01
Default Exp/Contr=0,0
English Units
Geom File=g01
Flow File=f01
Plan File=p01
BEGIN DESCRIPTION:
END DESCRIPTION:
DSS Export Rating Curves= 0
DSS Export Rating Curve Sorted= 0
DSS Export Volume Flow Curves= 0
DXF OffsetX= 0
DXF OffsetY= 0
DXF ScaleX= 0
DXF ScaleY= 0

--- PINECRK.p01 (plan) ---

Plan Title=Floodplain
Program Version=4.00
Geom File=g01
Flow File=f01
K Sum by GR=0
Std Step Tol=0.01
Critical Tol=0.01
Num of Std Step Trials=20
Max Error Tol=0.3
Flow Tol Ratio=0.001
Split Flow NTrial=30
Split Flow Tol=0.02
Split Flow Ratio=0.02
Log Output Level=0
Friction Slope Method=1
Unsteady Friction Slope Method=2
Unsteady Bridges Friction Slope Method=1
Global Log Level=0
CheckData=False
Run HTab=0
Run UNet=0
Run PostProcess=0
UNET Theta=0
UNET Theta Warmup=0
UNET ZTol=0
UNET ZSATol=0
UNET MxIter=0
UNET MaxInSteps=0
UNET DtIC=0
UNET DtMin=0
UNET MaxCRTS=0
UNET WFStab=0
UNET SFStab=0
UNET WFX=0
UNET SFX=0
UNET DSS MLevel=0
UNET DZMax Abort=0
UNET Convert EG Bridges=0
UNET Use Existing IB Tables=0
UNET Froude Limit=0
UNET Froude Power=0
Write IC File=0
Echo Input=False
Echo Output=False
Write Detailed=0

--- PINECRK.f01 (steady flow) ---

Flow Title=NFF Regression Equation
Program Version=4.00
Number of Profiles=1
Profile Names=P100yr
River Rch & RM=PINECRK,Main      ,27298
1079.751
River Rch & RM=PINECRK,Main      ,26498
1141.593
River Rch & RM=PINECRK,Main      ,21623.1
1255.626
River Rch & RM=PINECRK,Main      ,21223.1
1410.717
River Rch & RM=PINECRK,Main      ,20422.5
1425.052
River Rch & RM=PINECRK,Main      ,15609.6
1802.304
River Rch & RM=PINECRK,Main      ,15609.6
1582.965
River Rch & RM=PINECRK,Main      ,15304.5
2706.820
River Rch & RM=PINECRK,Main      ,11604.8
2805.562
River Rch & RM=PINECRK,Main      ,5068.2
3116.816
River Rch & RM=PINECRK,Main      ,104.5
3344.621
Boundary for River Rch & Prof#=PINECRK,Main      ,1
Up Type=0
Dn Type=3
Dn Slope=0.0126

--- PINECRK.g01 (geometry) ---

Geom Title=USGS 10m DEM
Program Version=4.10

River Reach=PINECRK         ,Main
Reach XY= 30
     1658236.928      270112.409     1658855.109      270538.079
     1660015.589      270306.492     1661536.885      271331.843
     1662045.959      271238.792     1662958.623      271720.605
     1663307.242       272535.98     1664276.965      273629.847
     1664876.354      274972.207      1664943.92       275472.69
     1664678.554      275607.534     1664379.889      276611.925
     1666274.164      278560.365     1667128.918      278700.508
      1667720.76      278561.524     1668266.273      277991.688
     1668933.398      277707.928     1669692.021      277975.473
     1669964.199      278239.543     1670323.242      278188.582
     1671085.339      278468.868     1672229.644      278346.098
     1674090.877       277255.07     1674389.693       277307.19
     1674550.683      277827.223     1674870.347      277909.455
     1676798.756      277251.596     1677004.916      277277.076
     1677435.767      277714.877     1677668.566      277709.086

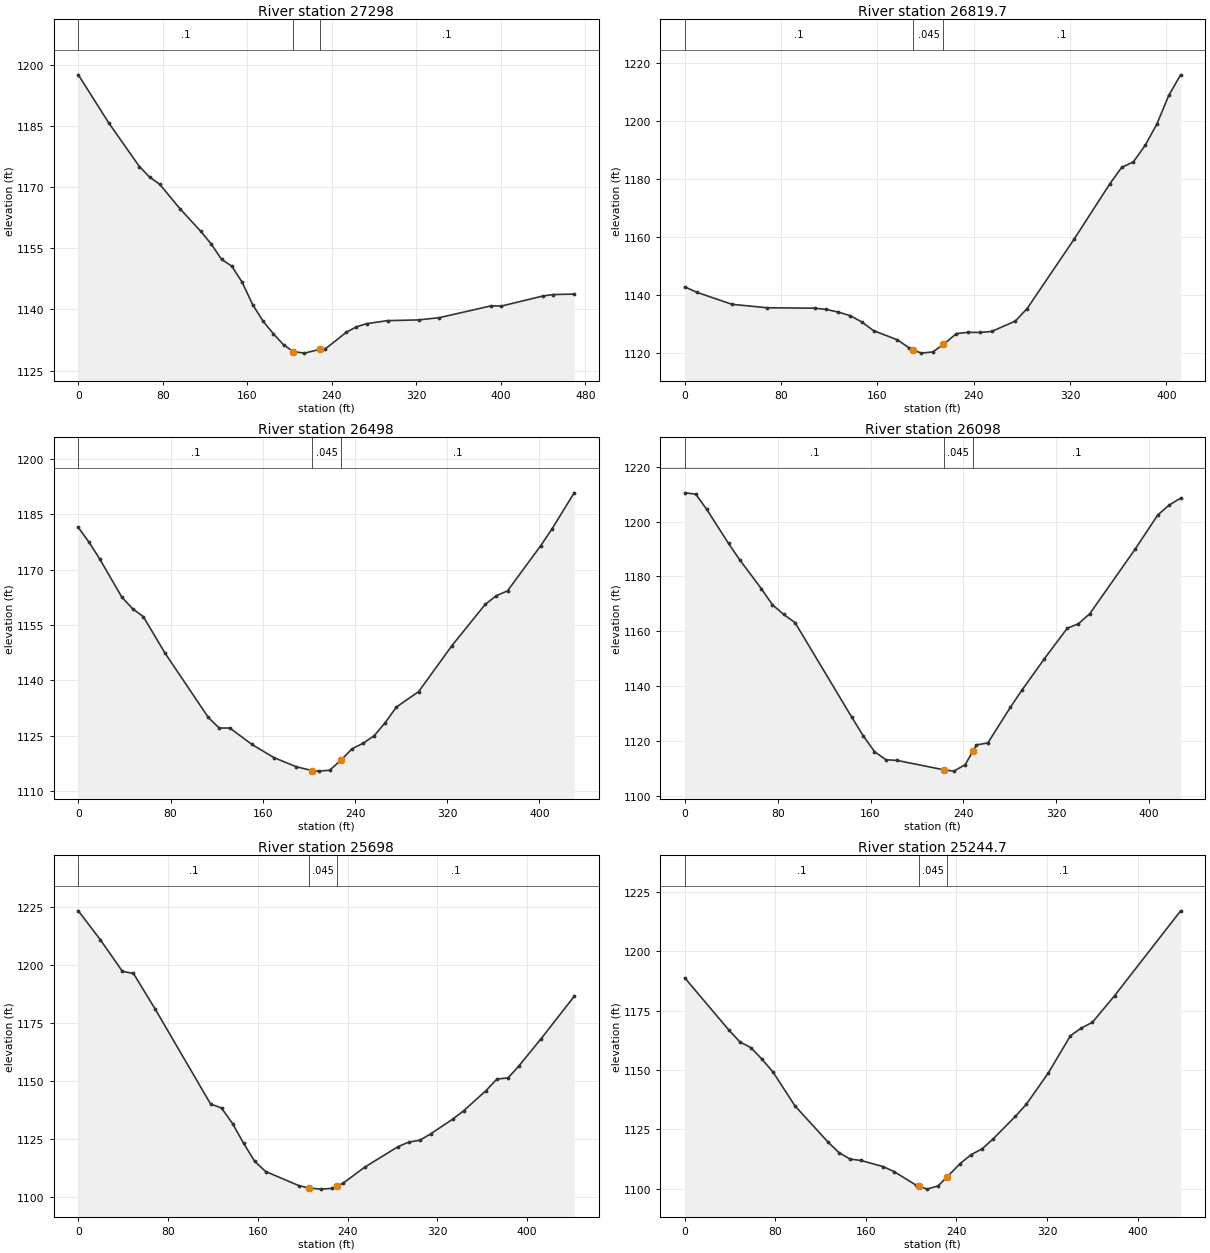
Type RM Length L Ch R = 1 ,27298   ,467.7,478.3,488.8
XS GIS Cut Line= 3
     1658167.452      270314.236     1658202.889       270224.66
     1658340.115      269877.783
#Sta/Elev= 30
       0 1197.63    28.9 1185.78    57.8 1175.11    67.4 1172.54    77.1 1170.73
    96.3 1164.72     116 1159.17   125.8 1156.08   135.6 1152.31   145.4 1150.61
   155.2 1146.62     165  1141.2   174.9 1137.12   184.7    1134   194.5 1131.27
   203.4 1129.66   214.1 1129.27   228.4 1130.19   233.8  1130.3   253.4 1134.34
   263.2 1135.72     273 1136.51   292.7 1137.25   322.1 1137.43   341.8 1137.98
   390.8 1140.89   400.6 1140.84   439.9 1143.31   449.7 1143.66   469.4 1143.77
#Mann= 3 , 0 , 0
       0      .1       0   203.4    .045       0   228.4      .1       0
Bank Sta=203.4,228.4
XS Rating Curve= 0 ,0
Exp/Cntr=0.3,0.1

Type RM Length L Ch R = 1 ,26819.7 ,344.8,321.5,298.3
XS GIS Cut Line= 2
     1658448.985      270567.401     1658731.112      270267.275
#Sta/Elev= 30
       0 1142.78     9.8 1140.94    39.2 1136.77    68.6 1135.58   107.9 1135.44
   117.7 1134.99   127.5  1134.1   137.3 1132.88   147.1 1130.68   156.9 1127.68
   176.5 1124.56   186.3 1121.79   189.9 1121.12   196.2 1119.96     206 1120.37
   214.9 1122.96   225.6 1126.68   235.4 1127.13   245.2 1127.08     255 1127.43
   274.6    1131   284.4 1135.32   323.6 1159.32   353.1 1178.28   362.9 1183.91
   372.7 1185.85   382.5 1191.56   392.3 1198.97   402.1 1208.77   411.9 1215.81
#Mann= 3 , 0 , 0
       0      .1       0   189.9    .045       0   214.9      .1       0
Bank Sta=189.9,214.9
XS Rating Curve= 0 ,0
Exp/Cntr=0.3,0.1

Type RM Length L Ch R = 1 ,26498   ,403.5,400,396.4
XS GIS Cut Line= 3
      1658899.64      270750.593     1658887.326      270610.205
     1658862.053      270322.095
#Sta/Elev= 30
       0 1181.47     9.4 1177.42    18.8 1172.81    37.6 1162.64      47 1159.46
    56.4 1157.28    75.2 1147.41   112.7 1129.98   122.1  1127.1   131.5 1127.08
   150.6 1122.63   169.8 1119.05   189.1 1116.59   203.1 1115.52   208.4  1115.4
     218 1115.64   228.1 1118.45   237.3 1121.44     247 1122.96   256.6 1124.99
   266.2 1128.54   275.9 1132.78   295.2 1136.96   324.1 1149.44     353 1160.64
   362.7 1162.99   372.3 1164.29   401.2 1176.58   410.9  1181.1   430.1 1190.87
#Mann= 3 , 0 , 0
       0      .1       0   203.1    .045       0   228.1      .1       0
Bank Sta=203.1,228.1
XS Rating Curve= 0 ,0
Exp/Cntr=0.3,0.1

Type RM Length L Ch R = 1 ,26098   ,400.8,400,399.2
XS GIS Cut Line= 3
      1659318.03      270668.556     1659301.871      270594.852
     1659226.542       270251.28
#Sta/Elev= 30
       0 1210.49     9.4 1210.02    18.9 1204.46    37.7 1192.02    47.2 1186.13
      66  1175.5    75.5 1169.66    85.2 1166.15      95 1163.15   143.8 1128.69
   153.6 1121.97   163.4 1116.14   173.2 1113.14   182.9  1112.9   223.2 1109.46
   231.8 1108.99   241.6 1111.36   248.2 1116.25   251.3 1118.55   261.1 1119.27
   280.6 1132.32   290.4 1138.49   309.9 1150.03   329.5 1161.09   339.2 1162.75
     349 1166.44   388.1 1190.01   407.6 1202.46   417.4 1206.04   427.2 1208.55
#Mann= 3 , 0 , 0
       0      .1       0   223.2    .045       0   248.2      .1       0
Bank Sta=223.2,248.2
XS Rating Curve= 0 ,0
Exp/Cntr=0.3,0.1

Type RM Length L Ch R = 1 ,25698   ,425.2,453,480.9
XS GIS Cut Line= 2
     1659713.655       270577.72     1659606.511      270149.138
#Sta/Elev= 30
       0 1223.32    19.6 1210.87    39.3 1197.24    49.1 1196.37    68.7 1180.83
   117.8 1140.17   127.6 1138.39   137.4 1131.72   147.3 1123.18   157.1 1115.46
   166.9 1111.06   196.3 1105.01   205.5 1103.95     216 1103.47   225.8 1103.78
   230.5  1104.8   235.6  1105.9   255.2 1112.93   284.7 1121.72   294.5 1123.74
   304.3  1124.5   314.2 1127.35   333.8 1133.68   343.6 1137.33   363.2 1145.87
     373 1150.89   382.9 1151.35   392.7 1156.61   412.3 1168.22   441.8 1186.48
#Mann= 3 , 0 , 0
       0      .1       0   205.5    .045       0   230.5      .1       0
Bank Sta=205.5,230.5
XS Rating Curve= 0 ,0
Exp/Cntr=0.3,0.1

Type RM Length L Ch R = 1 ,25244.7 ,371.2,357.5,343.7
XS GIS Cut Line= 2
     1659927.463      270515.663     1660228.136      270197.216
#Sta/Elev= 30
       0 1188.81    38.9 1166.84    48.7 1161.83    58.4  1159.4    68.1  1154.6
    77.9 1149.15    97.3 1134.88   126.5 1119.62   136.3 1115.09     146 1112.44
   155.7 1111.84   175.2 1109.27   184.9 1107.16   204.4 1101.42   206.7 1101.03
   214.1 1099.77   223.8 1101.15   231.7 1104.93   243.3 1110.56     253 1114.32
   262.8  1116.8   272.5    1121     292 1130.43   301.7 1135.53   321.2 1148.78
   340.6  1164.4   350.4  1167.7   360.1  1170.1   379.6 1181.27     438 1217.08
#Mann= 3 , 0 , 0
       0      .1       0   206.7    .045       0   231.7      .1       0
Bank Sta=206.7,231.7
XS Rating Curve= 0 ,0
Exp/Cntr=0.3,0.1

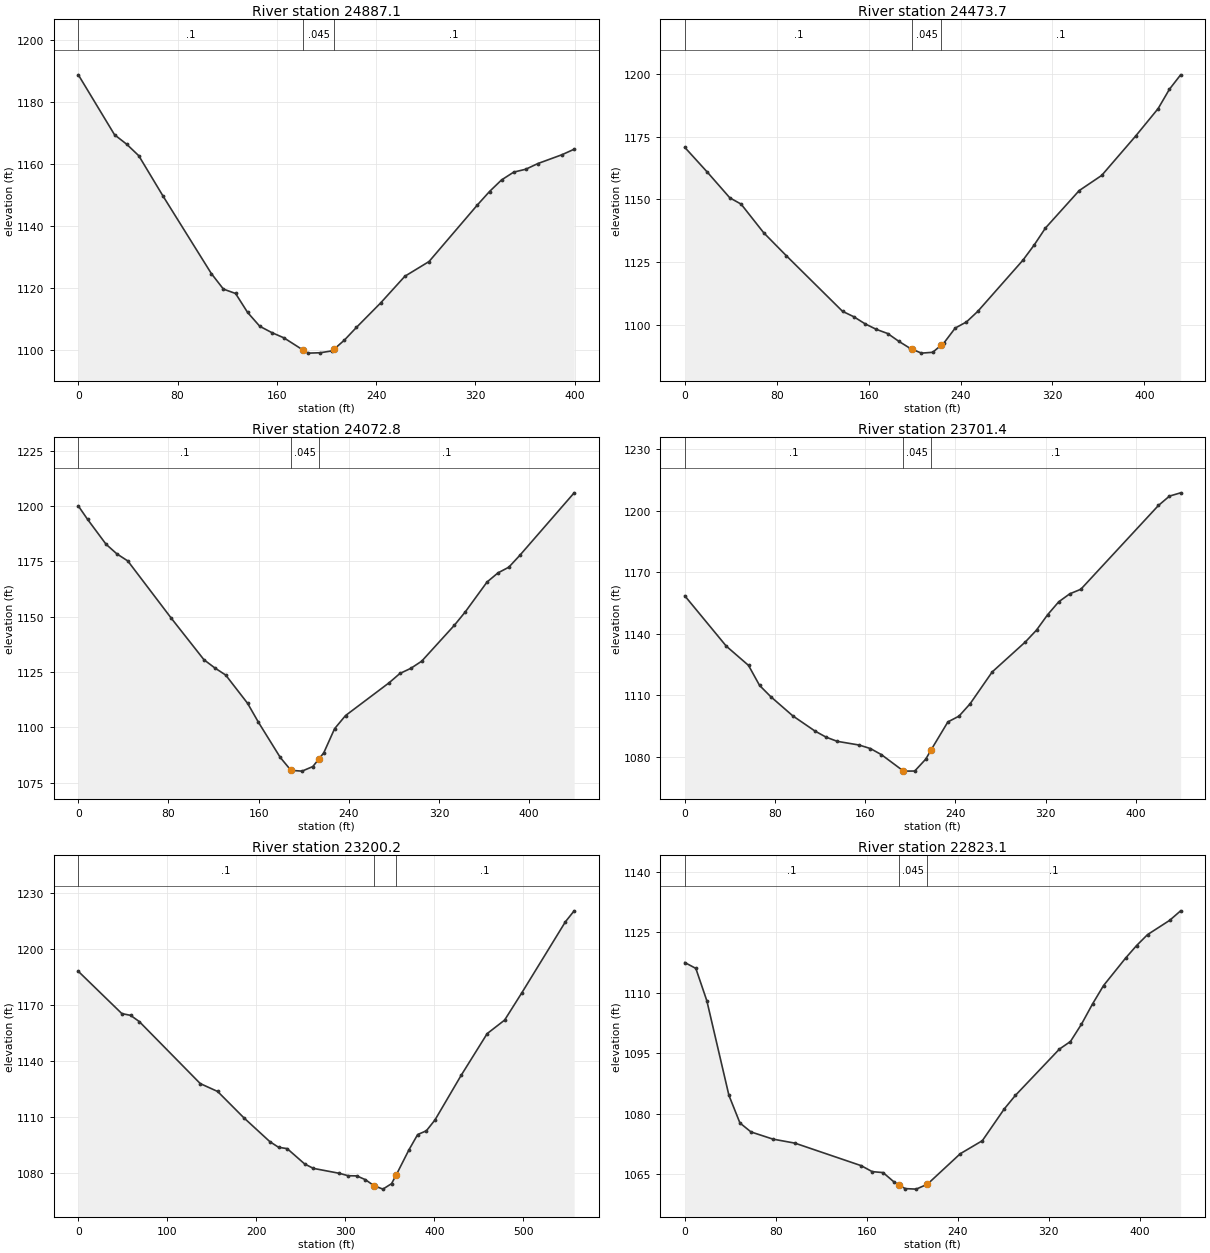
Type RM Length L Ch R = 1 ,24887.1 ,398.6,413.2,427.9
XS GIS Cut Line= 2
      1660331.03       270700.72     1660433.589      270314.618
#Sta/Elev= 30
       0 1188.83    29.2 1169.48      39 1166.43    48.7 1162.73    68.2 1149.74
   107.2 1124.69   116.9  1119.7   126.7 1118.28   136.4 1112.16   146.2  1107.7
   155.9 1105.66   165.6 1103.98   181.2    1100   185.1 1099.04   194.9 1099.16
   204.6 1099.78   206.2 1100.35   214.4 1103.25   224.1 1107.35   243.6 1115.24
   263.1 1123.84   282.6  1128.6   321.5 1146.83   331.3 1151.18     341 1154.92
   350.8 1157.44   360.5 1158.37   370.3 1160.21   389.8 1163.07   399.5 1164.83
#Mann= 3 , 0 , 0
       0      .1       0   181.2    .045       0   206.2      .1       0
Bank Sta=181.2,206.2
XS Rating Curve= 0 ,0
Exp/Cntr=0.3,0.1

Type RM Length L Ch R = 1 ,24473.7 ,410.7,400.7,390.7
XS GIS Cut Line= 2
     1660568.631       270873.83     1660873.807      270568.653
#Sta/Elev= 30
       0 1170.76    19.6 1160.89    39.2 1150.64      49 1148.14    68.7 1136.71
    88.3  1127.6   137.3  1105.4   147.1 1103.24   156.9 1100.42   166.8 1098.19
   176.6 1096.55   186.4 1093.41   196.2 1090.62     198 1090.27     206 1088.73
   215.8 1089.06     223 1091.82   225.6 1092.81   235.4 1098.73   245.2 1101.17
     255 1105.37   294.3 1125.77   304.1 1131.82   313.9 1138.58   343.3 1153.53
   362.9 1159.58   392.4 1175.25     412 1186.21   421.8  1193.9   431.6 1199.68
#Mann= 3 , 0 , 0
       0      .1       0     198    .045       0     223      .1       0
Bank Sta=198,223
XS Rating Curve= 0 ,0
Exp/Cntr=0.3,0.1

Type RM Length L Ch R = 1 ,24072.8 ,363.7,371.4,379.1
XS GIS Cut Line= 3
     1660946.512       271148.56     1660956.584      271126.131
     1661126.748        270747.2
#Sta/Elev= 30
       0 1200.02     8.2 1193.97    24.6 1182.73    34.2 1178.38    43.9 1175.18
    82.6 1149.24   111.5 1130.55   121.2 1126.84   130.8 1123.63   150.2 1110.88
   159.8 1102.34   179.2 1086.43   188.7  1080.6   198.5 1080.25   208.1 1082.32
   213.7 1085.89   217.8 1088.51   227.4 1099.41   237.1 1105.34   275.8 1120.16
   285.4 1124.37   295.1 1126.69   304.7 1129.91   333.7 1146.13   343.4 1152.19
   362.7 1165.67   372.4 1169.79     382 1172.36   391.7 1177.67     440 1205.95
#Mann= 3 , 0 , 0
       0      .1       0   188.7    .045       0   213.7      .1       0
Bank Sta=188.7,213.7
XS Rating Curve= 0 ,0
Exp/Cntr=0.3,0.1

Type RM Length L Ch R = 1 ,23701.4 ,527.1,501.2,475.3
XS GIS Cut Line= 3
     1661201.797      271329.127     1661219.246      271308.521
     1661485.922      270993.598
#Sta/Elev= 30
       0 1158.52    36.8 1133.96    56.5 1124.58    66.3 1114.81    76.1 1109.38
    95.8 1099.94   115.4 1092.56   125.3 1089.56   135.1 1087.53   154.7  1085.7
   164.6    1084   174.4 1081.01   193.4 1073.23     194 1072.98   203.9 1073.03
   213.7 1078.85   218.4 1083.33   233.3 1096.99   243.2 1099.83     253 1105.84
   272.6 1121.38   302.1 1136.07   311.9  1141.8   321.8 1149.33   331.6  1155.6
   341.4  1159.5   351.2 1161.72     420  1202.6   429.8 1207.18   439.7 1208.78
#Mann= 3 , 0 , 0
       0      .1       0   193.4    .045       0   218.4      .1       0
Bank Sta=193.4,218.4
XS Rating Curve= 0 ,0
Exp/Cntr=0.3,0.1

Type RM Length L Ch R = 1 ,23200.2 ,363.3,377,390.8
XS GIS Cut Line= 3
     1661799.551      271555.265     1661772.907      271430.839
      1661682.95      271010.731
#Sta/Elev= 30
       0 1188.06    48.9  1165.4    58.7 1164.47    68.5 1161.12     137 1127.88
   156.5 1123.66   185.8 1109.62   215.1 1096.78   224.9 1093.76   234.6 1093.03
   254.2 1084.82     264 1082.45   293.2  1079.8     303 1078.52   312.8 1078.42
   322.5 1076.37     332  1073.2   342.1 1071.33   351.8 1074.26     357  1078.9
   371.4 1092.44   381.1 1100.57   390.9  1102.6   400.6 1108.42   429.9 1132.26
   459.2 1154.68   478.8 1161.93   498.3 1176.69   547.1 1214.64   556.9 1220.49
#Mann= 3 , 0 , 0
       0      .1       0     332    .045       0     357      .1       0
Bank Sta=332,357
XS Rating Curve= 0 ,0
Exp/Cntr=0.3,0.1

Type RM Length L Ch R = 1 ,22823.1 ,390.7,399.9,409.2
XS GIS Cut Line= 2
      1662044.57       271447.03     1662167.971      271028.735
#Sta/Elev= 30
       0 1117.52     9.7 1116.07    19.4 1108.03    38.8  1084.6    48.5 1077.74
    58.2 1075.52    77.5 1073.74    96.9 1072.74   155.1 1067.16   164.8 1065.68
   174.4 1065.44   184.1  1063.1   188.3 1062.39   193.8 1061.47   203.5 1061.34
   213.3 1062.54   242.3 1070.12   261.7 1073.35     281 1081.23   290.7 1084.56
   329.5 1096.06   339.2 1097.94   348.9 1102.24   358.6 1107.24   368.3 1111.81
   387.7 1118.62   397.4 1121.74     407 1124.44   426.4 1127.97   436.1 1130.34
#Mann= 3 , 0 , 0
       0      .1       0   188.3    .045       0   213.3      .1       0
Bank Sta=188.3,213.3
XS Rating Curve= 0 ,0
Exp/Cntr=0.3,0.1

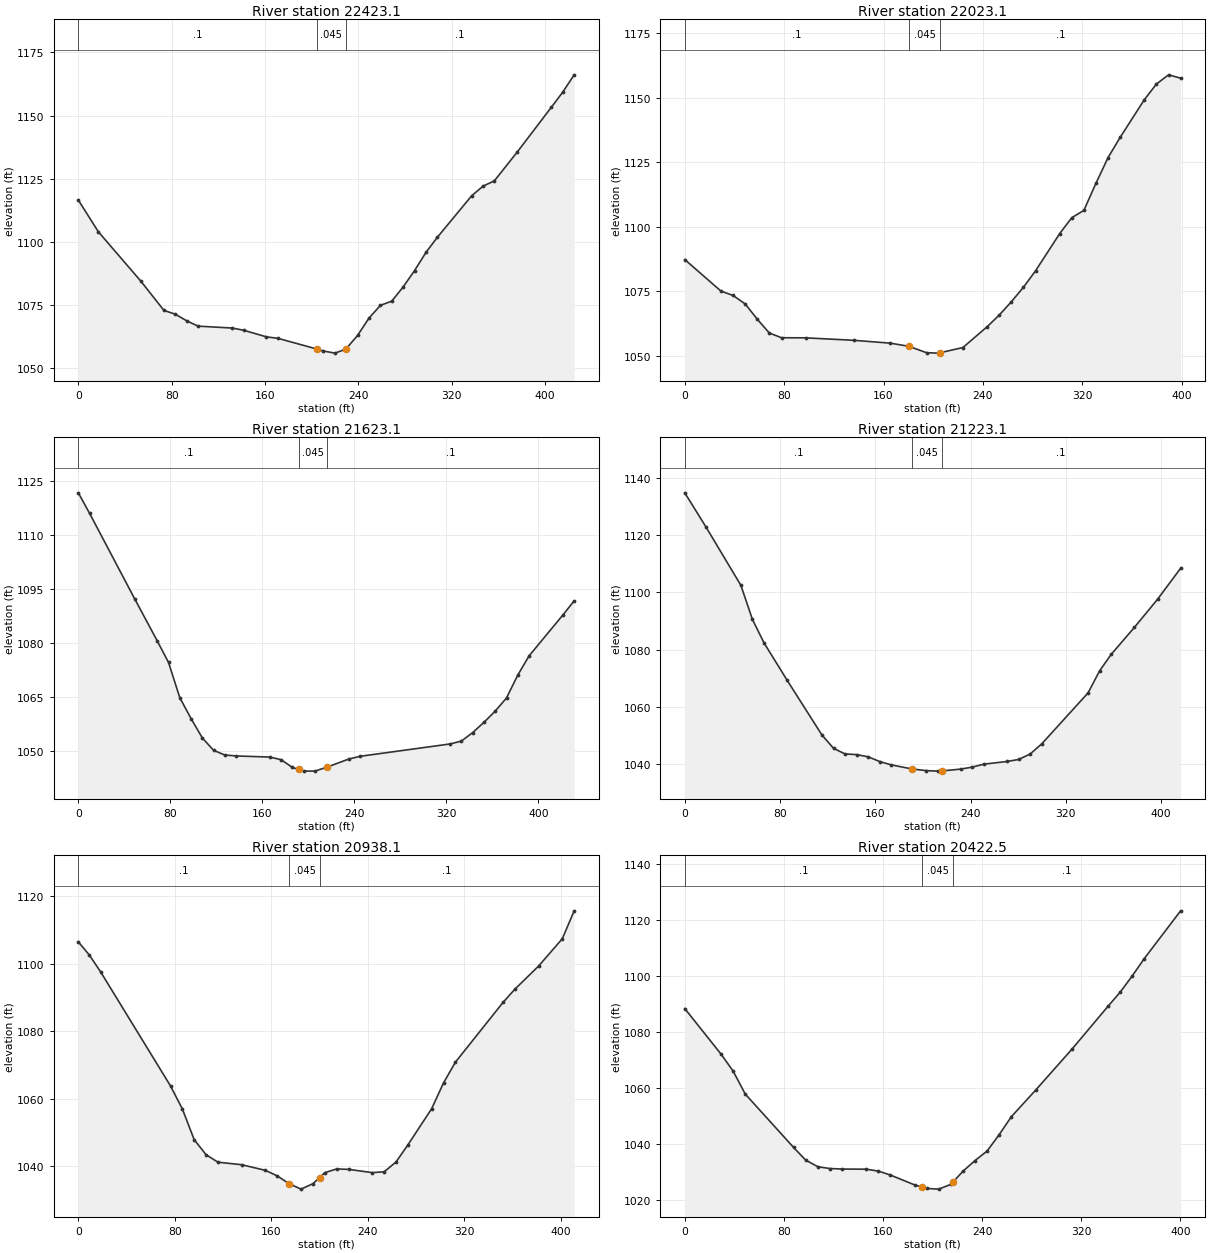
Type RM Length L Ch R = 1 ,22423.1 ,400,400,399.9
XS GIS Cut Line= 3
     1662327.262      271605.061     1662347.214      271577.218
     1662574.715      271259.741
#Sta/Elev= 30
       0 1116.54    17.1 1104.01    53.8  1084.3    73.3 1072.86    83.1 1071.34
    92.8 1068.75   102.6 1066.62   131.9 1065.87   141.7 1064.99   161.2 1062.37
     171  1061.8   204.1 1057.59     210 1056.78   219.8 1055.94   229.1 1057.49
   239.3 1062.98   249.1 1069.85   258.8 1074.84   268.6 1076.54   278.4 1082.21
   288.1 1088.64   297.9 1095.85   307.7 1101.86     337 1118.24   346.7 1122.02
   356.5 1124.17     376 1135.53   405.3 1153.29   415.1 1159.31   424.8 1166.11
#Mann= 3 , 0 , 0
       0      .1       0   204.1    .045       0   229.1      .1       0
Bank Sta=204.1,229.1
XS Rating Curve= 0 ,0
Exp/Cntr=0.3,0.1

Type RM Length L Ch R = 1 ,22023.1 ,384.3,399.9,415.5
XS GIS Cut Line= 2
     1662700.802      271756.256     1662932.483      271431.278
#Sta/Elev= 30
       0 1087.26    29.2 1075.02    38.9 1073.36    48.7 1070.04    58.4 1064.12
    68.1 1058.79    77.9 1056.98    97.3 1056.94   136.3 1055.98   165.5 1054.88
   180.4 1053.65   194.7 1051.17   204.4 1051.02   205.4 1051.15   223.9  1053.2
   243.4 1061.27   253.1 1065.77   262.8 1070.89   272.6 1076.56   282.3 1082.89
   301.8 1097.36   311.5 1103.51   321.2  1106.3     331 1116.88   340.7 1126.79
   350.4 1134.59   369.9 1149.22   379.6 1155.28   389.4 1158.85   399.1 1157.56
#Mann= 3 , 0 , 0
       0      .1       0   180.4    .045       0   205.4      .1       0
Bank Sta=180.4,205.4
XS Rating Curve= 0 ,0
Exp/Cntr=0.3,0.1

Type RM Length L Ch R = 1 ,21623.1 ,395.1,399.9,404.8
XS GIS Cut Line= 2
     1662873.156      271978.172     1663272.508      271816.043
#Sta/Elev= 30
       0 1121.64     9.8 1115.94      49 1092.23    68.6 1080.57    78.4  1074.6
    88.2 1064.83      98 1059.02   107.8 1053.66   117.6 1050.22   127.3 1048.94
   137.1 1048.67   166.5 1048.36   176.3 1047.63   186.1 1045.47   191.5 1044.92
   195.9 1044.48   205.7 1044.46   216.5 1045.61   235.1 1047.81   244.9 1048.57
   323.3    1052     333  1052.8   342.8 1055.15   352.6 1057.99   362.4 1061.11
   372.2 1064.76     382 1071.09   391.8 1076.42   421.2 1087.76     431 1091.67
#Mann= 3 , 0 , 0
       0      .1       0   191.5    .045       0   216.5      .1       0
Bank Sta=191.5,216.5
XS Rating Curve= 0 ,0
Exp/Cntr=0.3,0.1

Type RM Length L Ch R = 1 ,21223.1 ,295.7,284.8,273.8
XS GIS Cut Line= 3
     1663035.124      272297.344     1663043.176       272295.63
     1663442.432      272210.662
#Sta/Elev= 30
       0 1134.78      18  1122.7    47.1 1102.47    56.8 1090.55    66.6 1082.32
      86 1069.28   115.1 1050.24   124.9 1045.54   134.6 1043.58   144.3 1043.35
     154 1042.58   163.7 1040.93   173.5 1039.75   190.8 1038.34   202.6 1037.76
   212.3 1037.58   215.8 1037.64   231.8 1038.29   241.5 1038.99   251.2 1040.02
   270.6 1040.95   280.4 1041.65   290.1 1043.58   299.8 1047.12   338.7 1064.92
   348.4 1072.64   358.1 1078.35   377.6  1087.8     397 1097.59   416.4 1108.43
#Mann= 3 , 0 , 0
       0      .1       0   190.8    .045       0   215.8      .1       0
Bank Sta=190.8,215.8
XS Rating Curve= 0 ,0
Exp/Cntr=0.3,0.1

Type RM Length L Ch R = 1 ,20938.1 ,514.8,515.6,516.3
XS GIS Cut Line= 3
     1663147.184      272633.523     1663177.654      272612.533
     1663485.559      272400.421
#Sta/Elev= 30
       0 1106.52     9.2 1102.57    18.5  1097.6    76.4 1063.77    86.2 1056.96
      96 1047.84   105.9 1043.36   115.7 1041.16   135.4 1040.41   155.1 1038.73
   164.9 1037.08   174.9 1034.73   184.6 1033.17   194.4 1034.78   199.9  1036.6
   204.3 1038.05   214.1 1039.16     224 1039.03   243.6 1038.06   253.5 1038.32
   263.3 1041.23   273.1 1046.28   292.8 1057.02   302.7 1064.71   312.5 1070.83
   351.9 1088.53   361.7 1092.45   381.4 1099.33   401.1 1107.45   410.9 1115.72
#Mann= 3 , 0 , 0
       0      .1       0   174.9    .045       0   199.9      .1       0
Bank Sta=174.9,199.9
XS Rating Curve= 0 ,0
Exp/Cntr=0.3,0.1

Type RM Length L Ch R = 1 ,20422.5 ,425.9,421.7,417.6
XS GIS Cut Line= 2
      1663426.81      273036.359     1663760.894      272816.005
#Sta/Elev= 30
       0 1088.49    29.3  1072.2      39 1066.16    48.8 1057.95    87.8 1038.88
    97.6 1034.34   107.4 1031.99   117.1 1031.34   126.9 1031.16   146.4  1031.1
   156.2 1030.43   165.9 1029.02   185.5 1025.49   191.8 1024.67   195.2 1024.22
     205 1023.98   214.8  1025.7   216.8 1026.66   224.5 1030.37   234.3 1034.21
     244 1037.59   253.8 1043.48   263.6 1049.88   283.1 1059.32   312.4 1073.95
   341.6 1089.32   351.4 1094.35   361.2  1100.2   370.9 1106.39   400.2 1123.43
#Mann= 3 , 0 , 0
       0      .1       0   191.8    .045       0   216.8      .1       0
Bank Sta=191.8,216.8
XS Rating Curve= 0 ,0
Exp/Cntr=0.3,0.1

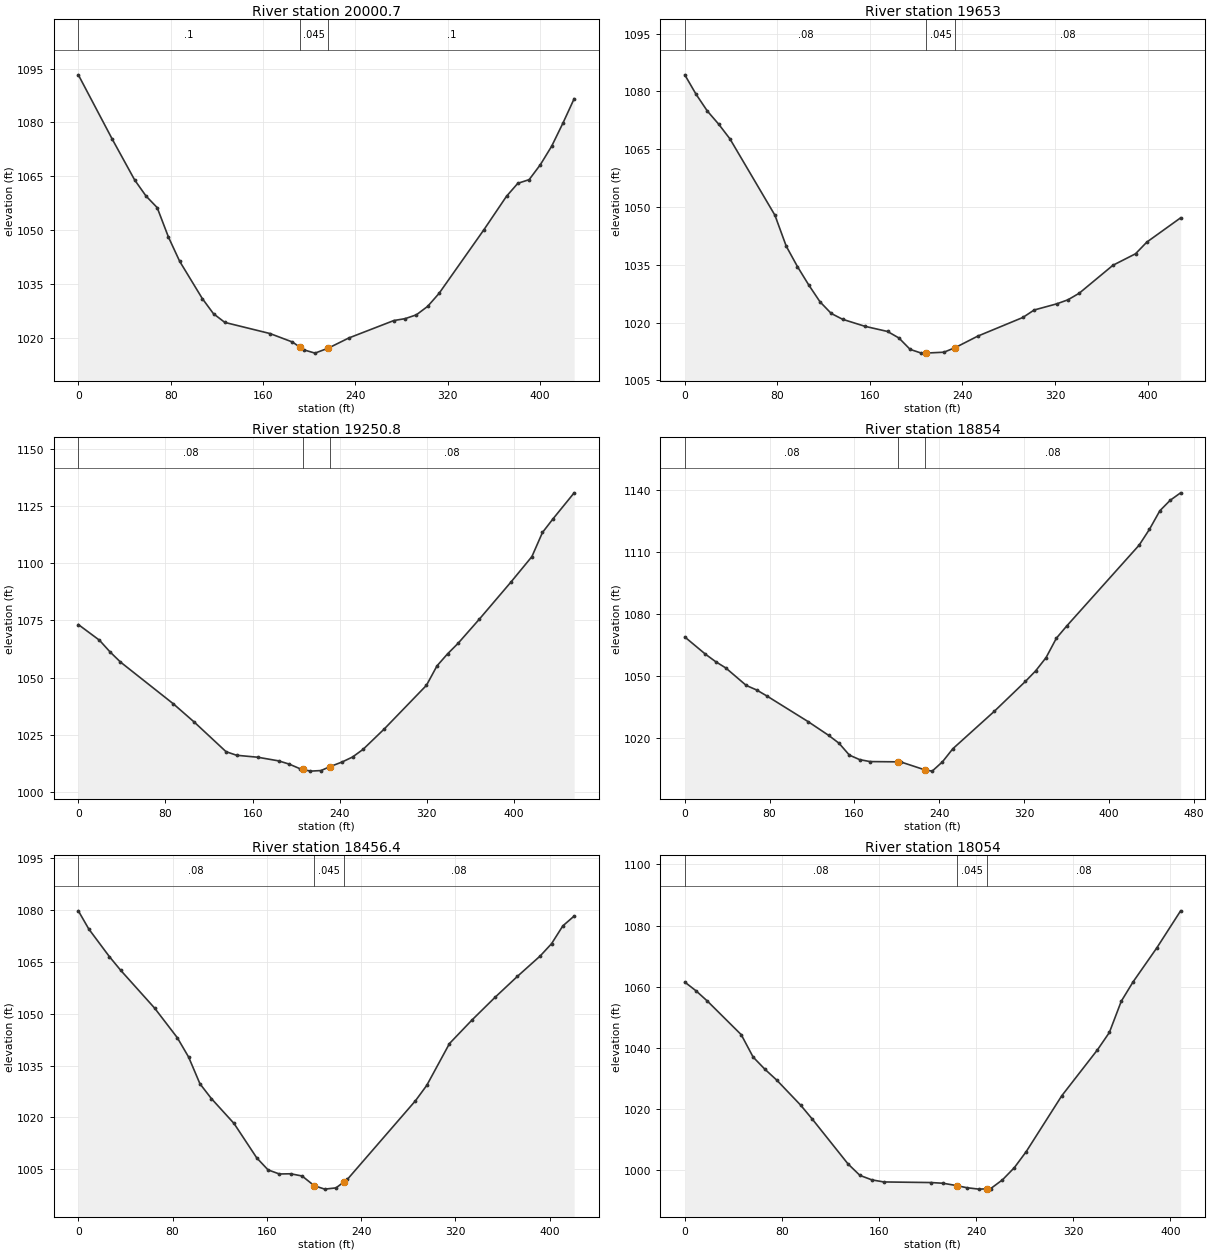
Type RM Length L Ch R = 1 ,20000.7 ,341.1,347.7,354.3
XS GIS Cut Line= 2
     1663730.502      273362.137     1664049.578      273074.618
#Sta/Elev= 30
       0 1093.25    29.3 1075.37    48.8 1063.95    58.6 1059.49    68.3 1056.25
    78.1 1048.01    87.8 1041.28   107.4  1030.9   117.1 1026.67   126.9 1024.26
     166 1021.16   185.5 1018.79   191.7 1017.41   195.2 1016.63     205  1015.7
   216.7 1017.12   234.3 1019.92   273.3 1024.78   283.1 1025.31   292.8 1026.37
   302.6 1028.73   312.4 1032.32   351.4 1050.12   370.9 1059.41   380.7 1063.02
   390.5 1064.04   400.2  1068.2     410 1073.35   419.8 1079.81   429.5  1086.6
#Mann= 3 , 0 , 0
       0      .1       0   191.7    .045       0   216.7      .1       0
Bank Sta=191.7,216.7
XS Rating Curve= 0 ,0
Exp/Cntr=0.3,0.1

Type RM Length L Ch R = 1 ,19653   ,399.2,402.2,405.3
XS GIS Cut Line= 2
     1663929.898       273579.53     1664306.789      273375.505
#Sta/Elev= 30
       0 1084.33     9.7  1079.3    19.5 1074.92    29.2 1071.55      39 1067.71
    77.9 1047.87    87.7 1039.82    97.4 1034.51   107.1 1029.77   116.9 1025.37
   126.6 1022.35   136.4 1020.84   155.8 1019.01   175.3 1017.67   185.1 1015.98
   194.8 1013.02   204.5 1012.05   208.9 1012.07     224 1012.29   233.9  1013.5
   253.2 1016.46   292.2 1021.31     302 1023.25   321.4 1024.84   331.2  1025.9
   340.9  1027.6   370.1 1034.87   389.6 1037.85   399.4 1040.89   428.6 1047.19
#Mann= 3 , 0 , 0
       0     .08       0   208.9    .045       0   233.9     .08       0
Bank Sta=208.9,233.9
XS Rating Curve= 0 ,0
Exp/Cntr=0.3,0.1

Type RM Length L Ch R = 1 ,19250.8 ,394.8,396.7,398.6
XS GIS Cut Line= 2
     1664115.647      273891.156     1664536.611      273718.015
#Sta/Elev= 30
       0 1073.17    19.4 1066.32      29 1061.27    38.7 1056.78    87.2 1038.54
   106.5 1030.52   135.6 1017.62   145.3 1016.05   164.6  1015.2     184 1013.59
   193.7 1012.17   203.4 1010.19   205.9 1009.91   213.1 1009.12   222.8 1009.37
   230.9 1011.06   242.1  1013.1   251.8  1015.3   261.5 1018.67   280.9 1027.56
   319.6 1046.62   329.3 1055.13     339 1060.38   348.6 1064.95     368 1075.44
   397.1  1091.7   416.4 1102.86   426.1  1113.4   435.8 1119.37   455.2 1130.73
#Mann= 3 , 0 , 0
       0     .08       0   205.9    .045       0   230.9     .08       0
Bank Sta=205.9,230.9
XS Rating Curve= 0 ,0
Exp/Cntr=0.3,0.1

Type RM Length L Ch R = 1 ,18854   ,401.5,397.7,393.9
XS GIS Cut Line= 3
     1664235.915      274248.686     1664336.883      274215.029
      1664679.66      274100.769
#Sta/Elev= 30
       0 1068.86    19.4 1060.56      29 1056.95    38.7 1053.86      58  1045.4
    67.7 1043.23    77.4 1040.33   116.2 1027.95   135.7 1021.26   145.5 1017.45
   155.3 1011.69     165 1009.51   174.8 1008.57   201.5 1008.44   204.1 1008.34
   226.5 1004.56   233.4 1003.95   243.1 1008.45   252.9 1014.79     292 1032.88
   321.3 1047.33     331 1052.44   340.8 1058.84   350.6 1068.27   360.3 1074.14
   428.7 1113.31   438.4 1120.95   448.2 1129.92     458 1135.01   467.8 1138.59
#Mann= 3 , 0 , 0
       0     .08       0   201.5    .045       0   226.5     .08       0
Bank Sta=201.5,226.5
XS Rating Curve= 0 ,0
Exp/Cntr=0.3,0.1

Type RM Length L Ch R = 1 ,18456.4 ,401.5,402.2,403
XS GIS Cut Line= 3
     1664428.964      274625.365     1664452.449      274613.621
     1664805.371      274437.132
#Sta/Elev= 30
       0 1079.74     8.8 1074.52    26.3 1066.52    35.9 1062.56    64.8 1051.58
      84 1043.04    93.6 1037.44   103.2 1029.72   112.9 1025.44   132.1 1018.25
   151.4 1008.29     161 1004.81   170.6 1003.62   180.2 1003.68   189.9 1003.04
   200.2 1000.23   209.1  999.24   218.7   999.6   225.2 1001.27   228.4 1002.09
   286.1  1024.8   295.7 1029.25     315 1041.36   334.2  1048.2   353.5 1054.67
   372.7  1060.8     392 1066.69   401.6 1070.23   411.2 1075.39   420.8 1078.23
#Mann= 3 , 0 , 0
       0     .08       0   200.2    .045       0   225.2     .08       0
Bank Sta=200.2,225.2
XS Rating Curve= 0 ,0
Exp/Cntr=0.3,0.1

Type RM Length L Ch R = 1 ,18054   ,355.3,360,364.7
XS GIS Cut Line= 3
     1664605.816      274971.433     1664648.068      274952.047
     1664977.069      274801.099
#Sta/Elev= 30
       0 1061.52     9.3 1058.65    18.6 1055.31    46.5 1044.32    56.3    1037
      66 1033.02    75.8 1029.45    95.4  1021.3   105.2 1016.64   134.5 1002.05
   144.3  998.31   154.1  996.85   163.9  996.17     203  995.97   212.8  995.74
   224.1  994.97   232.4  994.28   242.2  993.82   249.1  993.92   251.9  993.96
   261.7  996.85   271.5 1000.84   281.3 1006.09   310.6 1024.36     340 1039.38
   349.8 1045.05   359.6 1055.26   369.3 1061.57   388.9 1072.72   408.5 1084.82
#Mann= 3 , 0 , 0
       0     .08       0   224.1    .045       0   249.1     .08       0
Bank Sta=224.1,249.1
XS Rating Curve= 0 ,0
Exp/Cntr=0.3,0.1

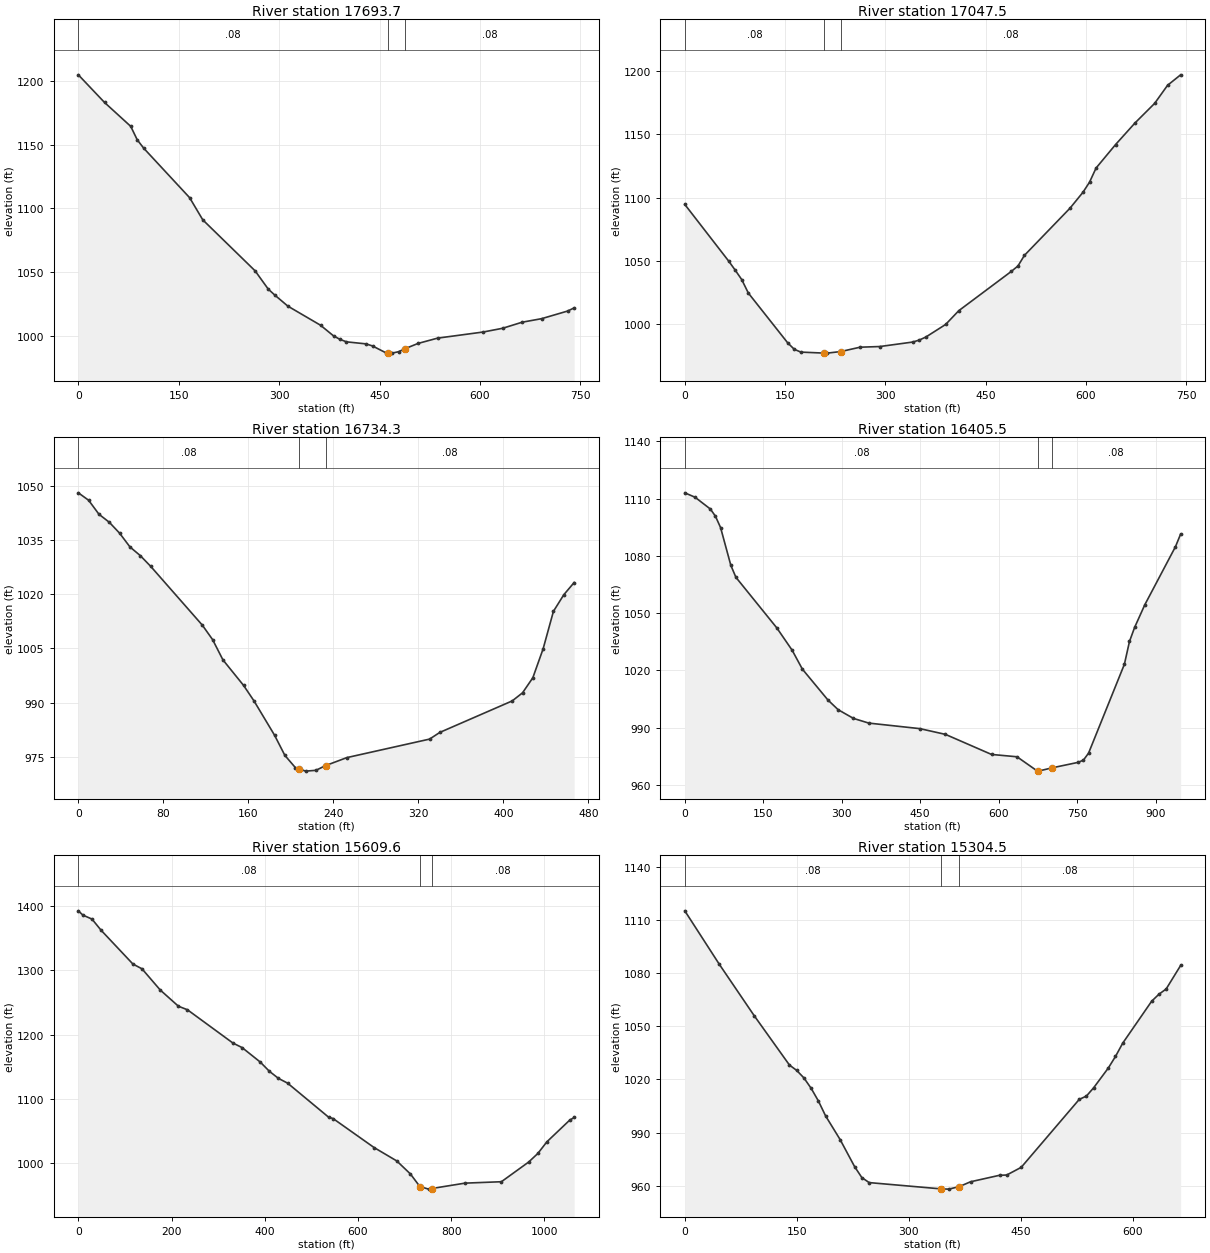
Type RM Length L Ch R = 1 ,17693.7 ,627.4,645.9,664.6
XS GIS Cut Line= 3
     1664434.018      275344.307     1664754.333      275254.761
     1665147.374      275144.883
#Sta/Elev= 30
       0 1204.97    39.1 1183.27    78.3 1164.45      88 1153.87    97.8 1147.21
   166.3 1108.36   185.9 1090.97   264.1 1050.87   283.7 1036.52   293.5 1031.83
     313 1023.13   361.8 1008.13   381.2  999.76   390.9  997.01   400.6  995.06
   429.8  993.46   439.5  991.82   458.9  986.59   462.7  986.43   468.6  986.19
   478.4   987.3   487.7   989.6   507.5  993.81   536.6  997.97   604.7 1002.78
   633.8 1005.72     663  1010.5   692.1 1013.28     731 1019.28   740.7 1021.77
#Mann= 3 , 0 , 0
       0     .08       0   462.7    .045       0   487.7     .08       0
Bank Sta=462.7,487.7
XS Rating Curve= 0 ,0
Exp/Cntr=0.3,0.1

Type RM Length L Ch R = 1 ,17047.5 ,314.7,313.1,311.5
XS GIS Cut Line= 4
     1664471.383      275610.897     1664542.631      275635.187
      1664943.02      275771.687     1665173.308      275850.197
#Sta/Elev= 30
       0 1094.55    65.9 1049.58    75.3 1042.67    85.1 1035.19      95 1024.52
     154  985.06   163.8  980.01   173.6  977.81   208.4  977.02     213     977
   233.4  978.26   262.2  981.69   291.7  982.21   340.9  985.76   350.7  987.32
   360.6  989.74   390.1  999.66   409.8 1010.56   488.4 1041.62   498.3 1045.89
     508 1054.31   576.2 1091.62   595.6 1104.21   605.4 1112.19   615.1 1123.31
   644.3 1141.89   673.5 1159.04   702.7 1174.42   722.1 1188.76   741.6 1197.02
#Mann= 3 , 0 , 0
       0     .08       0   208.4    .045       0   233.4     .08       0
Bank Sta=208.4,233.4
XS Rating Curve= 0 ,0
Exp/Cntr=0.3,0.1

Type RM Length L Ch R = 1 ,16734.3 ,328.5,328.8,329.2
XS GIS Cut Line= 2
     1664373.384      275895.983     1664816.755      276041.639
#Sta/Elev= 30
       0 1048.09     9.7 1046.03    19.4 1042.16    29.2 1039.92    38.9 1036.89
    48.6  1033.1    58.3  1030.7    68.1 1027.73   116.7 1011.44   126.4 1007.42
   136.1 1001.82   155.6  994.72   165.3  990.47   184.7  980.95   194.4  975.36
   204.2     972   207.8  971.63   213.9     971   223.6  971.22   232.8  972.54
   252.8  974.75   330.6  979.87   340.3  981.73   408.4  990.45   418.1  992.69
   427.8  996.86   437.5 1004.89   447.2 1015.27     457 1019.88   466.7 1023.25
#Mann= 3 , 0 , 0
       0     .08       0   207.8    .045       0   232.8     .08       0
Bank Sta=207.8,232.8
XS Rating Curve= 0 ,0
Exp/Cntr=0.3,0.1

Type RM Length L Ch R = 1 ,16405.5 ,826.3,795.7,765.1
XS GIS Cut Line= 2
     1663826.165      276051.375     1664729.768      276337.955
#Sta/Elev= 30
       0 1113.03    19.6 1110.72    48.9 1104.53    58.6 1100.76    68.4 1094.82
      88 1075.03    97.7 1068.75   175.9 1042.23   205.2 1030.53   224.8  1020.6
   273.6 1004.44   293.2  999.33   322.5  994.77   351.8  992.31   449.6   989.4
   498.4  986.39   586.4  975.88   635.2  974.65   674.3  967.13   676.2  967.15
   701.2  968.79   752.5  971.75   762.3  972.96     772  976.56   840.5 1023.16
   850.2 1035.09     860 1042.45   879.6 1054.39   938.2 1084.83     948 1091.41
#Mann= 3 , 0 , 0
       0     .08       0   676.2    .045       0   701.2     .08       0
Bank Sta=676.2,701.2
XS Rating Curve= 0 ,0
Exp/Cntr=0.3,0.1

Type RM Length L Ch R = 1 ,15609.6 ,307.5,305,302.5
XS GIS Cut Line= 2
     1664074.839      277477.022     1664828.161      276725.856
#Sta/Elev= 30
       0 1392.64     9.8 1385.97    29.3 1379.79    48.8 1362.46   117.1 1309.87
   136.6 1302.43   175.7 1269.48   214.7 1244.26   234.2 1238.67   331.8  1186.9
   351.4 1179.88   390.4 1157.34   409.9    1143   429.4 1131.97     449 1124.57
   536.8 1071.73   546.6 1069.47   634.4 1024.45   683.2 1003.56   712.5  983.28
   732.8  963.67   751.5   959.7   757.8   960.6   829.6  969.02   907.7  971.21
   966.2 1001.84   985.8 1015.13  1005.3  1033.3  1054.1 1066.95  1063.8 1071.16
#Mann= 3 , 0 , 0
       0     .08       0   732.8    .045       0   757.8     .08       0
Bank Sta=732.8,757.8
XS Rating Curve= 0 ,0
Exp/Cntr=0.3,0.1

Type RM Length L Ch R = 1 ,15304.5 ,397.5,398.4,399.4
XS GIS Cut Line= 3
     1664624.966      277391.146     1664702.615      277298.677
      1665052.25      276882.311
#Sta/Elev= 30
       0 1115.13    46.4 1084.86    92.9 1056.01   140.2 1028.11   149.9 1025.08
   159.6 1020.84   169.3 1014.96     179 1007.84   188.7  999.37   208.1  986.06
   227.5  970.79   237.2  964.61     247  961.76     343  958.22   353.8  958.07
     368  959.53   382.9  962.22   421.7  965.88   431.4  966.03   450.8  970.37
   528.5 1008.69   538.2 1010.61   547.9 1015.29   567.4 1026.36   577.1 1032.93
   586.8 1040.44   625.6 1064.12   635.3 1068.05     645 1071.01   664.4 1084.29
#Mann= 3 , 0 , 0
       0     .08       0     343    .045       0     368     .08       0
Bank Sta=343,368
XS Rating Curve= 0 ,0
Exp/Cntr=0.3,0.1

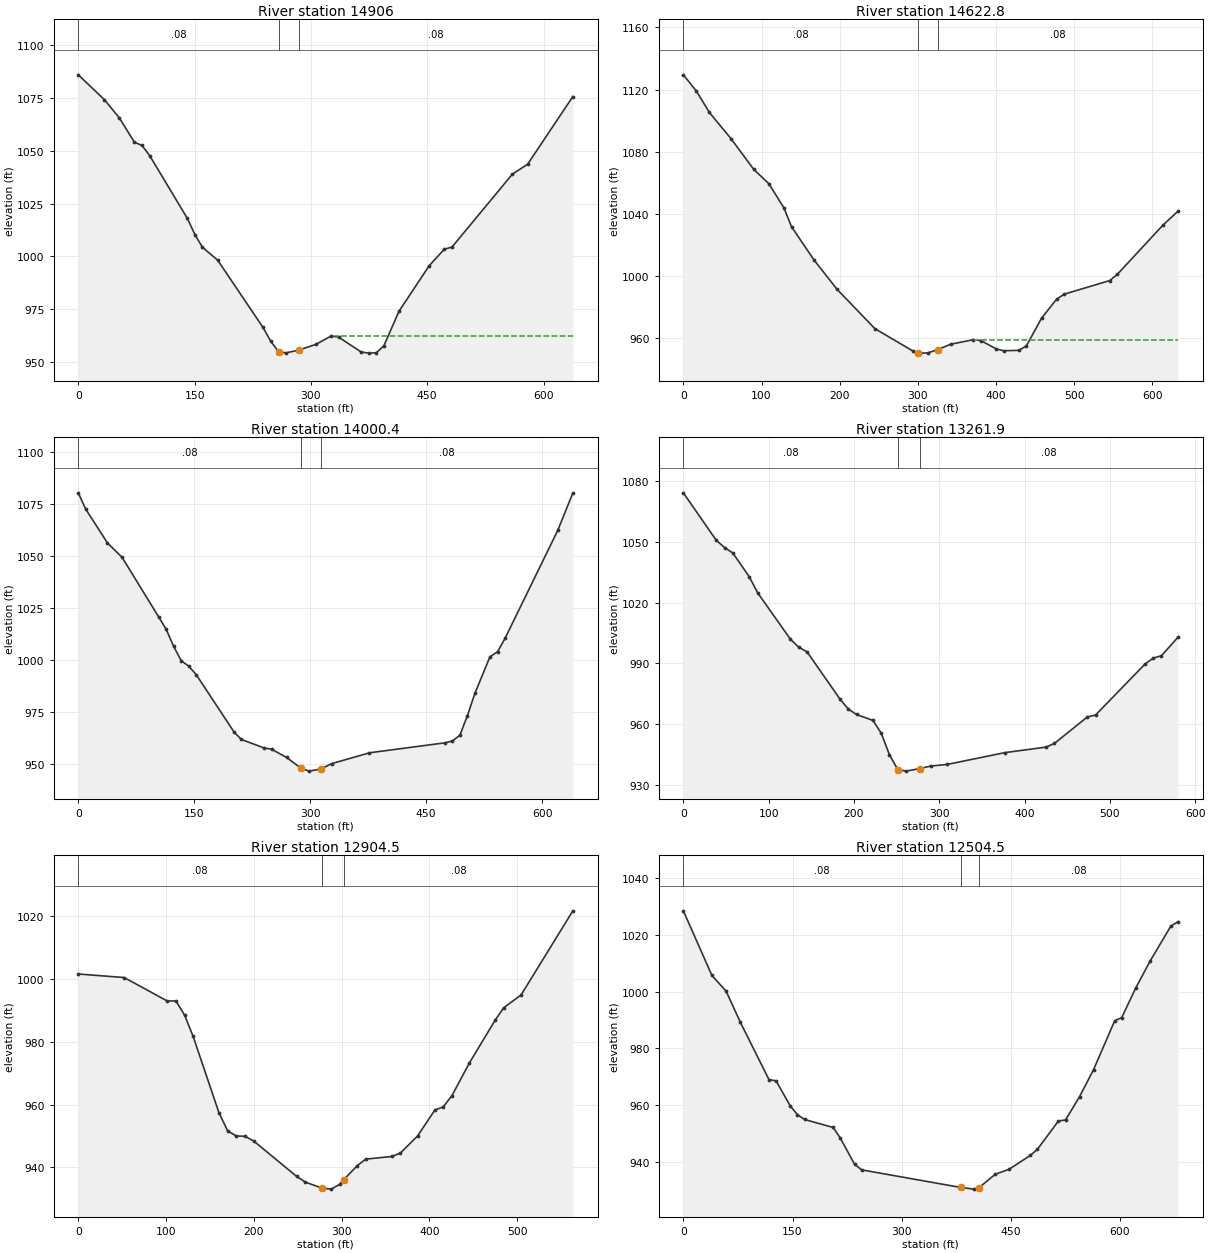
Type RM Length L Ch R = 1 ,14906   ,275.9,283.2,290.4
XS GIS Cut Line= 3
     1664959.975      277592.152     1664975.841      277574.528
     1665386.736      277118.112
#Sta/Elev= 30
       0  1085.8    33.5 1074.14      53 1065.43    72.4 1053.97    82.2 1052.43
      92 1047.68   140.7 1017.94   150.4 1010.34   160.2 1004.28   179.7  998.27
   238.2  966.48   247.9  960.12   257.7  955.23   259.5  955.08   267.4  954.41
   284.5  955.75   306.4  958.45   325.9  962.38   335.6  961.92   364.9  954.83
   374.6  954.32   384.4  954.51   394.1  957.78   413.6  974.11   452.6  995.65
   472.1 1003.44   481.9 1004.42   559.8 1038.87   579.4 1043.53   637.8 1075.54
#Mann= 3 , 0 , 0
       0     .08       0   259.5    .045       0   284.5     .08       0
#XS Ineff= 2 , 0
                          328.75          962.31
Permanent Ineff=
       F       F
Bank Sta=259.5,284.5
XS Rating Curve= 0 ,0
Exp/Cntr=0.3,0.1

Type RM Length L Ch R = 1 ,14622.8 ,629.3,622,614.8
XS GIS Cut Line= 3
     1665073.275       277765.22     1665108.086      277742.651
     1665604.196      277421.014
#Sta/Elev= 30
       0 1129.54    16.6 1119.14    33.2 1105.37    60.9 1088.52      90 1068.74
   109.3 1059.52   128.7 1043.94   138.4 1031.75   167.5 1010.21   196.6  991.58
     245  966.27   293.5  951.93   300.5  950.91   303.2  950.52   312.9  950.66
   325.5  952.84     342  956.24     371  959.18   380.7  958.58   400.1  953.24
   409.8  952.06   429.2   952.3   438.9  955.26   458.3  973.07   477.6  985.29
   487.4  988.46   545.5  997.22   555.2 1001.22   613.4  1032.8   632.7 1041.79
#Mann= 3 , 0 , 0
       0     .08       0   300.5    .045       0   325.5     .08       0
#XS Ineff= 2 , 0
                          370.45          959.16
Permanent Ineff=
       F       F
Bank Sta=300.5,325.5
XS Rating Curve= 0 ,0
Exp/Cntr=0.3,0.1

Type RM Length L Ch R = 1 ,14000.4 ,745.9,738.1,730.3
XS GIS Cut Line= 3
      1665537.07      278248.169     1665606.553       278171.11
     1665965.383      277773.156
#Sta/Elev= 30
       0 1080.37     9.4 1072.69    37.7  1056.3    56.6 1049.42   103.8 1020.83
   113.5 1014.91   123.2 1006.74     133  999.74   142.7  997.11   152.5  993.04
   201.2  965.58   210.9  961.85   240.2   957.8   249.9  957.17   269.4  953.21
   288.3  947.97   298.6  946.64   313.3  947.61   327.8  950.24   376.6  955.45
     474  960.23   483.7  961.13   493.5  963.84   503.2  973.25     513   984.1
   532.4 1001.59   542.2 1004.02   551.9 1010.43   620.1 1062.34   639.6  1080.3
#Mann= 3 , 0 , 0
       0     .08       0   288.3    .045       0   313.3     .08       0
Bank Sta=288.3,313.3
XS Rating Curve= 0 ,0
Exp/Cntr=0.3,0.1

Type RM Length L Ch R = 1 ,13261.9 ,365.6,357.3,349
XS GIS Cut Line= 3
     1666125.463       278778.68     1666146.673      278735.283
     1666380.115      278257.639
#Sta/Elev= 30
       0 1074.14    38.6  1050.7    48.3 1047.14      58 1044.47    77.3 1032.72
      87 1024.91   125.6 1001.89   135.3  997.99     145  995.72   183.6  972.42
   193.3  967.53     203  964.81   222.3  961.88     232  955.59   241.6  944.98
   251.3  937.71     252  937.65     261  936.88     277   938.1     290  939.39
   309.3  940.18     377  946.01   425.3  948.73     435  950.53   473.6  963.57
   483.3  964.56   541.3   989.7   550.9   992.6   560.6  993.82   579.9  1002.9
#Mann= 3 , 0 , 0
       0     .08       0     252    .045       0     277     .08       0
Bank Sta=252,277
XS Rating Curve= 0 ,0
Exp/Cntr=0.3,0.1

Type RM Length L Ch R = 1 ,12904.5 ,401.2,400,398.9
XS GIS Cut Line= 3
     1666538.073      278867.431     1666540.138      278854.675
     1666628.165      278311.085
#Sta/Elev= 30
       0 1001.52    52.3  1000.4   101.4  992.93   111.3  992.95   121.1  988.48
   130.9  981.68   160.4  957.34   170.3   951.6   180.1  950.02   189.9  949.91
   199.8  948.44   248.9  937.14   258.8  935.34   277.6  933.43   288.3  933.11
   298.1  934.66   302.6  936.12   317.8  940.56   327.6  942.65   357.1  943.49
   366.9  944.54   386.6  949.99   406.3  958.24   416.1  959.32   425.9  962.88
   445.6  973.19   475.1  986.85   484.9  990.82   504.6  994.85   563.6 1021.61
#Mann= 3 , 0 , 0
       0     .08       0   277.6    .045       0   302.6     .08       0
Bank Sta=277.6,302.6
XS Rating Curve= 0 ,0
Exp/Cntr=0.3,0.1

Type RM Length L Ch R = 1 ,12504.5 ,414.6,399.6,384.6
XS GIS Cut Line= 3
     1666921.947       279083.36     1666950.576      278840.016
      1667001.35      278408.438
#Sta/Elev= 30
       0 1028.45    39.2 1005.69    58.8  1000.1    78.4  989.12   117.6  968.97
   127.4  968.54     147  959.65   156.8  956.61   166.6  954.91   205.8   952.1
   215.6  948.39   235.2  939.16     245  937.16   381.4  930.95   399.5  930.37
   406.4  930.92   428.5   935.6   447.8   937.4   476.8  942.26   486.4  944.38
   515.4  954.39   525.1  954.74   544.4  962.96   563.7  972.52   592.7   989.7
   602.3  990.82   621.6 1001.25     641 1010.61   669.9 1023.09   679.6 1024.59
#Mann= 3 , 0 , 0
       0     .08       0   381.4    .045       0   406.4     .08       0
Bank Sta=381.4,406.4
XS Rating Curve= 0 ,0
Exp/Cntr=0.3,0.1