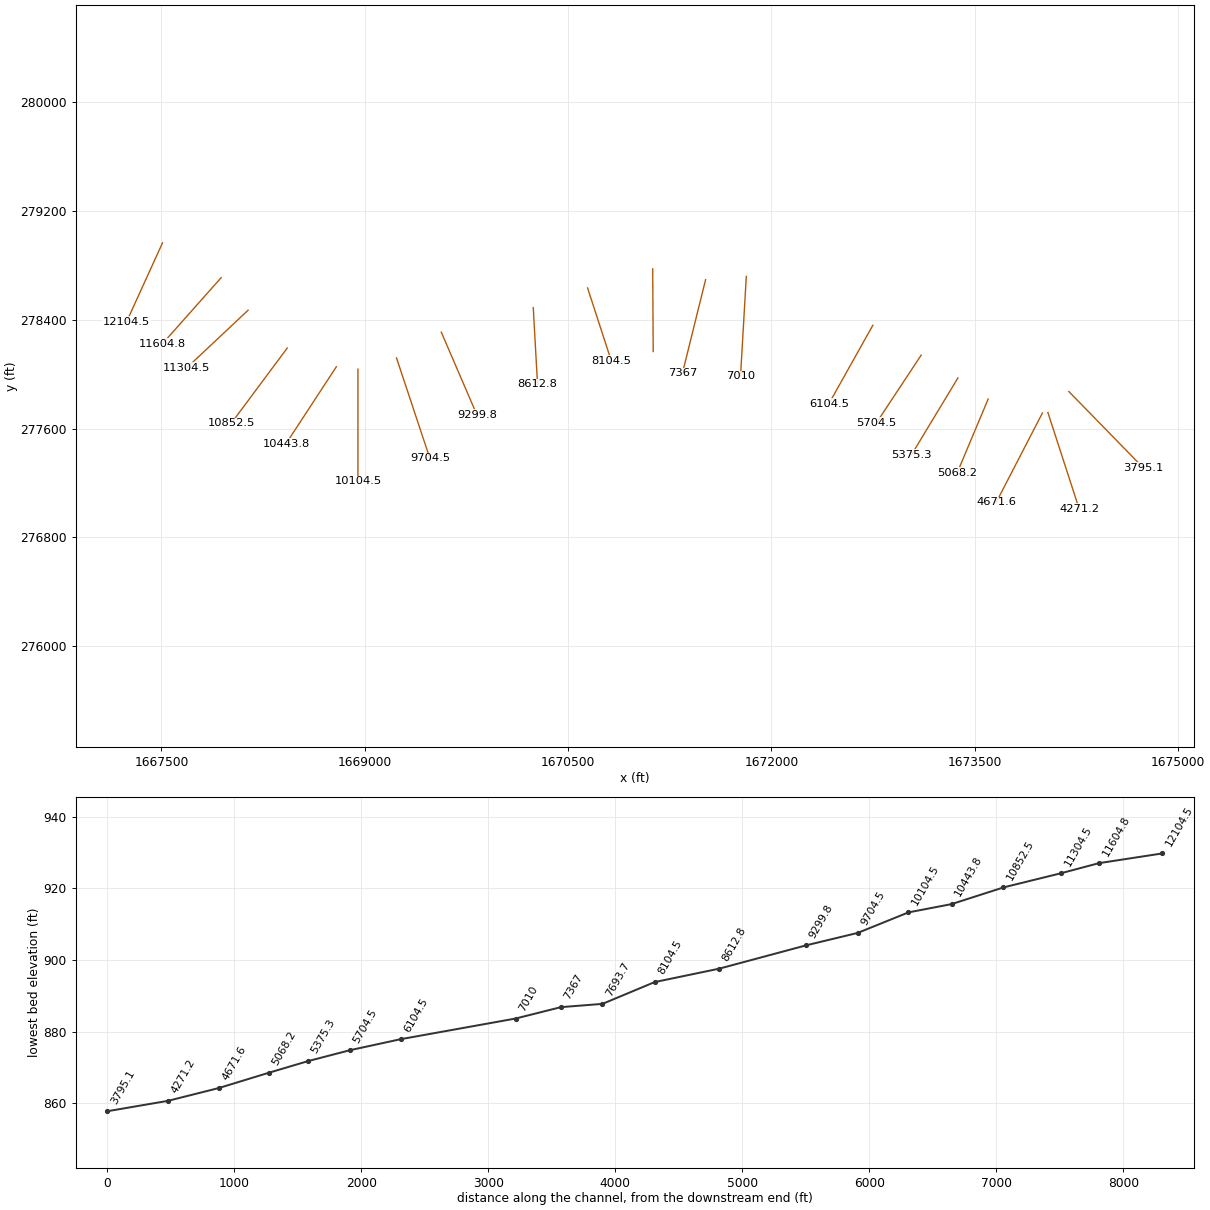
HEC-RAS study PINECRK.prj: PINECRK

--- PINECRK.g01 (geometry) --- (continued)

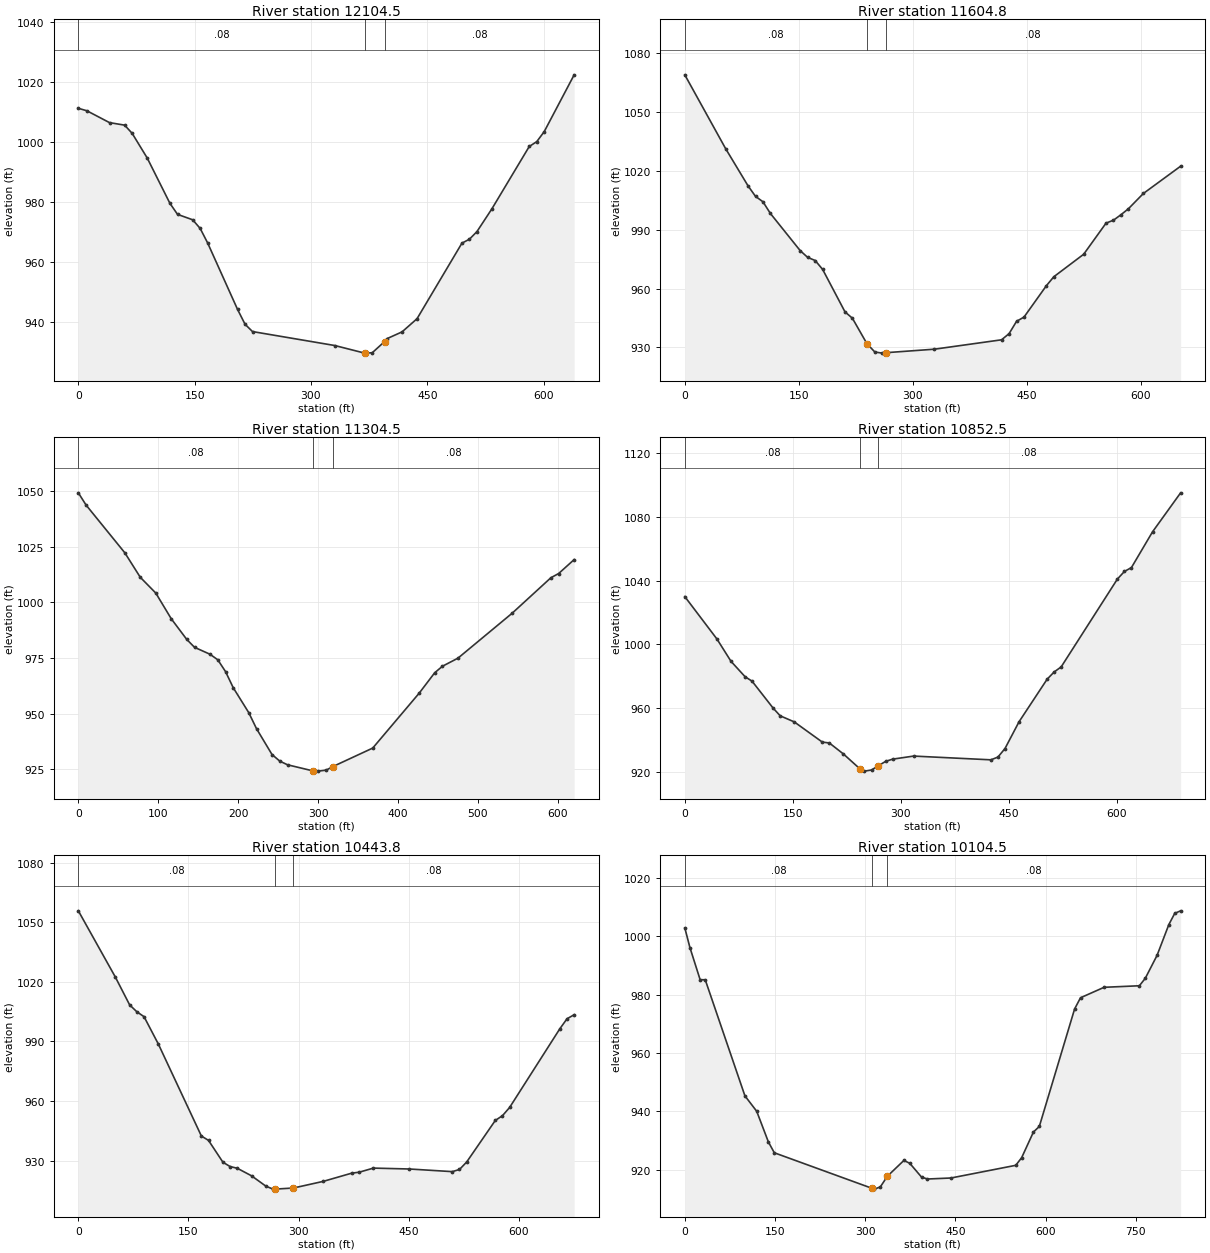
Type RM Length L Ch R = 1 ,12104.5 ,506.7,499.8,485.9
XS GIS Cut Line= 4
       1667508.5       278965.32     1667507.991      278964.207
     1667443.242      278822.421     1667242.898      278383.718
#Sta/Elev= 30
       0 1011.16      11 1010.34    40.2  1006.4    59.7 1005.56    69.4 1002.84
    88.9   994.6   118.1  979.57   127.9   975.9   147.4   974.1   157.1  971.23
   166.7  966.42   205.3  944.31     215  939.36   224.6  936.93   330.7  932.29
   369.3  929.76     370  929.77     379  929.88     395  933.62   398.2  934.59
   417.5  936.83   436.8  941.21   494.7  966.33   504.3  967.63     514  970.15
   533.3  977.73   581.5  998.47   591.2 1000.08   600.8 1003.41   639.4 1022.29
#Mann= 3 , 0 , 0
       0     .08       0     370    .045       0     395     .08       0
Bank Sta=370,395
XS Rating Curve= 0 ,0
Exp/Cntr=0.3,0.1

Type RM Length L Ch R = 1 ,11604.8 ,303.2,300.3,297.3
XS GIS Cut Line= 3
     1667941.365      278709.536     1667938.256      278706.048
     1667507.401      278222.659
#Sta/Elev= 30
       0 1069.04    53.7 1031.38    83.2 1012.38      93 1007.04   102.8 1004.27
   112.6   998.3   151.8  979.33   161.6   975.9   171.5   974.3   181.3  969.76
   210.7  948.11   220.5  944.82   239.5   931.9     250   927.6   259.8  927.04
   264.5  927.26   328.4  929.05   416.7  933.84   426.6  937.01   436.4  943.27
   446.2  945.43   475.6  961.43   485.4  966.01   524.7   977.5   554.1  993.37
   563.9  994.88   573.7  997.65   583.5 1000.69   603.2  1008.5   652.2 1022.42
#Mann= 3 , 0 , 0
       0     .08       0   239.5    .045       0   264.5     .08       0
Bank Sta=239.5,264.5
XS Rating Curve= 0 ,0
Exp/Cntr=0.3,0.1

Type RM Length L Ch R = 1 ,11304.5 ,447.1,452,456.9
XS GIS Cut Line= 2
     1668139.468      278469.671     1667686.688      278045.698
#Sta/Elev= 30
       0 1049.29     9.7 1043.79    58.2 1022.32    77.5 1011.33    96.9 1004.24
   116.3  992.66   135.7  983.38   145.4  979.85   164.8  976.73   174.5  974.23
   184.2  968.92   193.8  961.69   213.2   950.5   222.9   943.3   242.3  931.68
     252  928.71   261.7  927.06   293.2  924.34   300.4  924.21   310.2  924.67
   318.2  926.22   368.3  934.57   426.4  959.24   445.8  968.41   455.5  971.35
   474.9  974.97   542.8   995.2   591.2 1011.13   600.9 1013.02   620.3 1019.29
#Mann= 3 , 0 , 0
       0     .08       0   293.2    .045       0   318.2     .08       0
Bank Sta=293.2,318.2
XS Rating Curve= 0 ,0
Exp/Cntr=0.3,0.1

Type RM Length L Ch R = 1 ,10852.5 ,406.7,408.4,410.2
XS GIS Cut Line= 3
     1668428.517      278191.905     1668419.306      278179.564
     1668016.692      277640.178
#Sta/Elev= 30
       0 1029.95    44.7 1003.24    64.2  989.24    83.7  979.59    93.4  976.79
   122.7  959.83   132.5  955.01     152   951.2     191  938.49   200.7  937.96
   220.2  931.06   243.2  921.69   249.5  920.26   259.3  920.97   268.2  923.48
   278.8  926.37   288.5  927.78   317.8  929.72   425.1  927.36   434.8  929.09
   444.6  934.44   464.1  951.26   503.1  978.01   512.9  982.59   522.6  985.74
   600.7 1040.96   610.4 1045.72   620.2 1048.18   649.5 1070.65   688.5 1095.15
#Mann= 3 , 0 , 0
       0     .08       0   243.2    .045       0   268.2     .08       0
#XS Ineff= 2 , 0
                          320.73          929.32
Permanent Ineff=
       F       F
Bank Sta=243.2,268.2
XS Rating Curve= 0 ,0
Exp/Cntr=0.3,0.1

Type RM Length L Ch R = 1 ,10443.8 ,323.6,339.4,355.3
XS GIS Cut Line= 3
     1668790.553      278054.076      1668773.61      278028.263
     1668419.976      277489.499
#Sta/Elev= 30
       0 1055.77    50.4 1022.42    69.9 1008.38    79.7 1004.93    89.5 1002.45
     109  988.66   167.6  942.34   177.3  940.15   196.9  929.17   206.6  926.98
   216.4  926.12   235.9  922.31   255.5  917.08   265.2   915.6     268  915.61
     293  916.16   333.6  919.51   372.6  923.67   382.4  924.11   401.9  926.19
   450.8  925.74   509.3  924.41   519.1   925.5   528.9  929.25   567.9  950.19
   577.7  952.61   587.4  956.73   655.8  996.37   665.6 1001.41   675.3 1003.44
#Mann= 3 , 0 , 0
       0     .08       0     268    .045       0     293     .08       0
Bank Sta=268,293
XS Rating Curve= 0 ,0
Exp/Cntr=0.3,0.1

Type RM Length L Ch R = 1 ,10104.5 ,390.6,399.7,408.8
XS GIS Cut Line= 3
     1668949.945      278036.547     1668949.923      277985.532
     1668949.585       277211.97
#Sta/Elev= 30
       0 1002.94     8.5  996.19    25.5  985.15      34  985.12     100  945.29
   119.6     940   139.1  929.44   148.9  925.76     312  913.52   315.4  913.29
   325.2  914.06     337  917.73   364.4  923.14   374.2  922.14   393.7  917.42
   403.5  916.76   442.7  917.11   550.4  921.46   560.2  924.07   579.8  932.88
   589.6   934.8   648.3  975.12   658.1  978.95   697.3  982.54     756  983.07
   765.8  985.62   785.4  993.49     805 1004.06   814.8 1007.91   824.6 1008.78
#Mann= 3 , 0 , 0
       0     .08       0     312    .045       0     337     .08       0
#XS Ineff= 2 , 0
                          364.26          922.71
Permanent Ineff=
       F       F
Bank Sta=312,337
XS Rating Curve= 0 ,0
Exp/Cntr=0.3,0.1

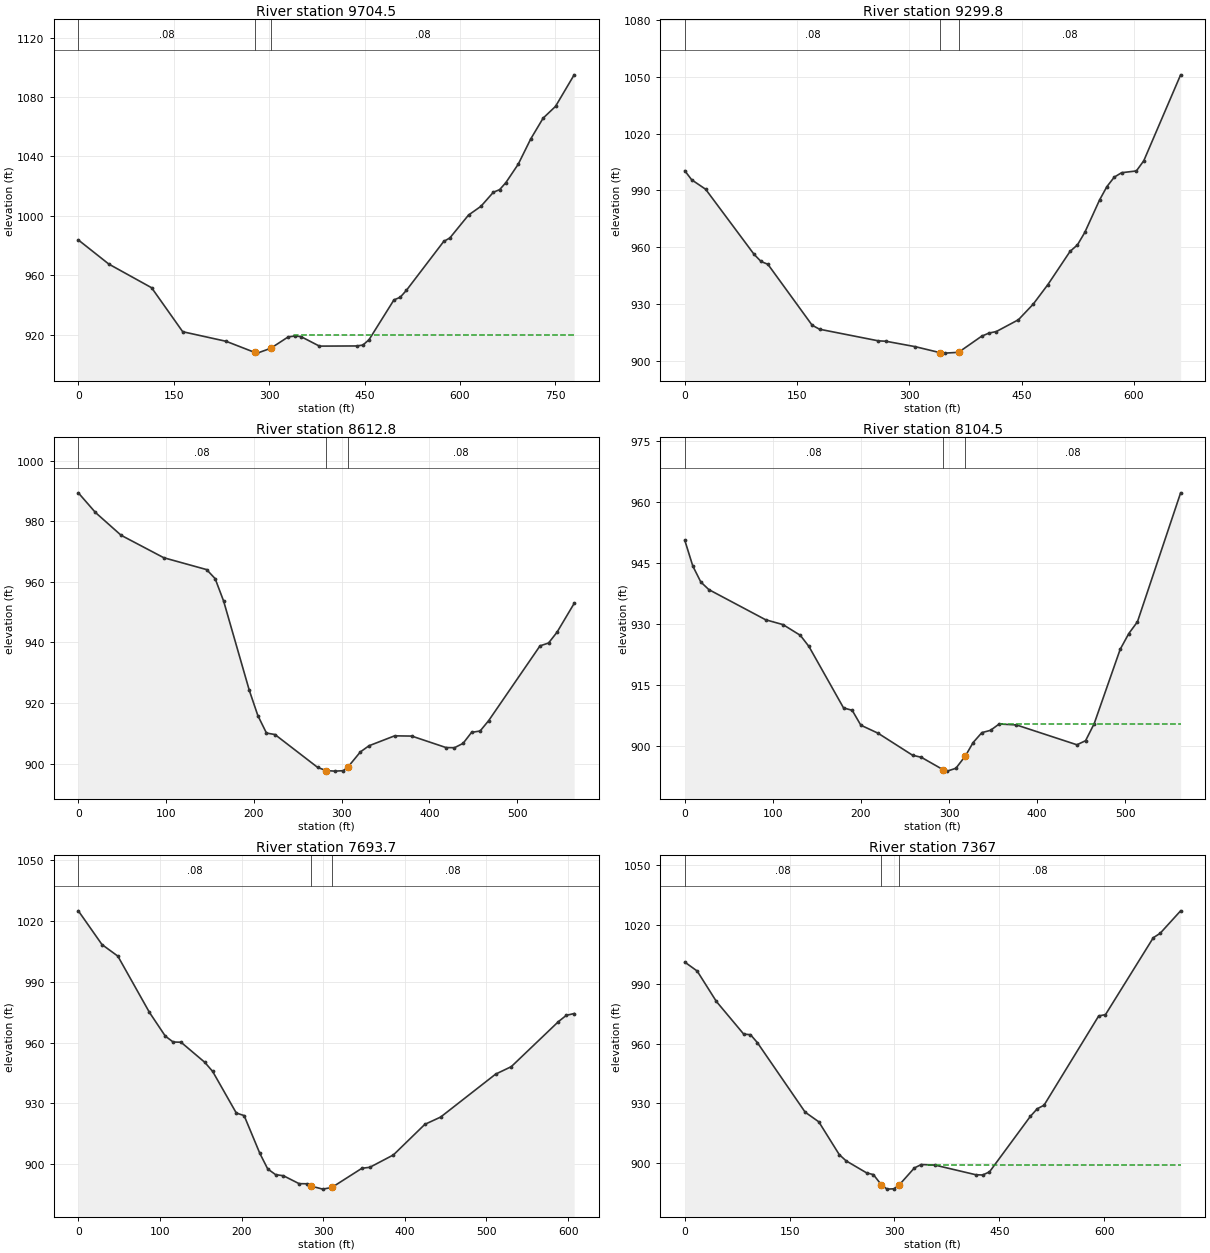
Type RM Length L Ch R = 1 ,9704.5  ,402.5,404.8,407
XS GIS Cut Line= 3
     1669234.344      278119.247     1669270.781      278009.936
     1669480.847      277379.737
#Sta/Elev= 30
       0  983.75      48  967.49   115.2  951.58   164.1  921.97   232.4  915.51
   277.4  908.02   281.3  907.56   302.4   910.8   330.1  918.53   339.9  919.02
   349.7  918.75     379  912.28   437.6  912.39   447.4  912.99   457.1  916.64
   496.2   943.4     506  945.15   515.8  949.84   574.4  982.74   584.1   985.1
   613.4  1000.5     633 1006.42   652.5 1015.87   662.3 1017.61     672 1022.26
   691.6 1034.76   711.1 1051.65   730.7 1065.74   750.2 1073.67   779.5 1094.91
#Mann= 3 , 0 , 0
       0     .08       0   277.4    .045       0   302.4     .08       0
#XS Ineff= 2 , 0
                          339.06          919.52
Permanent Ineff=
       F       F
Bank Sta=277.4,302.4
XS Rating Curve= 0 ,0
Exp/Cntr=0.3,0.1

Type RM Length L Ch R = 1 ,9299.8  ,695.7,686.5,677
XS GIS Cut Line= 3
     1669564.735      278308.471     1669608.759       278206.58
     1669827.366      277700.626
#Sta/Elev= 30
       0 1000.36     9.2  995.58    27.8  990.61    92.5  956.26   101.8  952.48
     111  950.98     170  918.87   179.9  916.72   258.6  910.58   268.5  910.38
   307.8  907.51   340.6  904.37   347.2   904.1   365.6  904.52   396.4  913.02
   406.3  914.69   416.1   915.5   445.6  921.73   465.3  929.94     485  940.32
   514.5  957.77   524.4  961.23   534.2   967.8   553.9   984.9   563.7  991.96
   573.6     997   583.4  999.33   603.1 1000.26     613 1005.64   662.2 1050.99
#Mann= 3 , 0 , 0
       0     .08       0   340.6    .045       0   365.6     .08       0
Bank Sta=340.6,365.6
XS Rating Curve= 0 ,0
Exp/Cntr=0.3,0.1

Type RM Length L Ch R = 1 ,8612.8  ,501.5,508.2,515.3
XS GIS Cut Line= 2
      1670243.15      278489.082     1670274.464      277924.829
#Sta/Elev= 30
       0  989.36    19.5  982.88    48.7  975.37    97.4  967.95   146.2  964.04
   155.9  961.07   165.6  953.65   194.9  924.17   204.6  915.89   214.4  910.13
   224.1  909.64   272.8  898.79   282.4  897.75   292.3  897.57     302  897.71
   307.4  898.97   321.5  903.92   331.3  905.94   360.5  909.21     380  909.13
     419  905.35   428.7  905.29   438.5  906.73   448.2  910.36   457.9   910.8
   467.7  914.24   526.2  938.89   535.9  939.82   545.6   943.4   565.1  952.89
#Mann= 3 , 0 , 0
       0     .08       0   282.4    .045       0   307.4     .08       0
#XS Ineff= 2 , 0
                          369.07          909.16
Permanent Ineff=
       F       F
Bank Sta=282.4,307.4
XS Rating Curve= 0 ,0
Exp/Cntr=0.3,0.1

Type RM Length L Ch R = 1 ,8104.5  ,419.3,410.7,402.2
XS GIS Cut Line= 3
     1670643.634      278633.718     1670669.094      278555.748
     1670818.337      278098.686
#Sta/Elev= 30
       0  950.57     9.1  944.25    18.2  940.32    27.3  938.46    91.8  931.04
   111.5  929.85   131.1  927.22   140.9  924.48   180.2  909.36     190  908.78
   199.8  905.12   219.4  903.14   258.6  897.72   268.5  897.22   293.6  894.12
   297.9  893.82   307.7  894.52   318.6  897.59   327.3  900.86   337.2  903.29
     347  903.85   356.8  905.41   376.4  905.18   445.1   900.3   454.9   901.3
   464.7   905.5   494.2  923.78     504  927.66   513.8  930.55   562.8  962.26
#Mann= 3 , 0 , 0
       0     .08       0   293.6    .045       0   318.6     .08       0
#XS Ineff= 2 , 0
                          358.08          905.46
Permanent Ineff=
       F       F
Bank Sta=293.6,318.6
XS Rating Curve= 0 ,0
Exp/Cntr=0.3,0.1

Type RM Length L Ch R = 1 ,7693.7  ,333.6,326.7,319.9
XS GIS Cut Line= 3
     1671124.054      278773.822     1671125.201      278589.938
     1671127.844       278166.43
#Sta/Elev= 30
       0 1024.95      29 1008.31    48.4 1002.62    87.1  974.88   106.5  963.21
   116.1  960.28   125.8  960.17   154.8   950.3   164.5   945.8   193.5  925.27
   203.1     924   222.4  905.32     232   897.7   241.6   894.9   251.3  894.33
   270.5  890.43   280.1  890.38   285.5  889.21   299.4  887.74   310.5  888.55
   347.5  898.04   357.1   898.5     386  904.61   424.5  919.68   443.8  923.26
   511.2  944.44   530.4  948.13   588.2  970.35   597.8  973.42   607.4  974.31
#Mann= 3 , 0 , 0
       0     .08       0   285.5    .045       0   310.5     .08       0
Bank Sta=285.5,310.5
XS Rating Curve= 0 ,0
Exp/Cntr=0.3,0.1

Type RM Length L Ch R = 1 ,7367    ,351.7,356.9,362
XS GIS Cut Line= 3
     1671514.163      278694.421      1671505.62      278660.048
     1671343.053      278006.005
#Sta/Elev= 30
       0 1001.14    17.7  996.65    45.2  981.32    84.3  964.88      94  964.59
   103.8  960.61   172.2  925.58   191.7  920.73     221  904.21   230.8  901.07
   260.1  895.02   269.8  894.15   281.2  889.03   289.4  886.83   299.1     887
   306.2  888.71   328.4  897.47   338.2  899.21   357.7  898.95   416.3  894.08
   426.1  893.94   435.9   895.5   494.5  923.51   504.2  927.27     514  929.09
   592.2  974.04   601.9   974.7   670.3 1013.42   680.1 1015.64   709.4 1026.96
#Mann= 3 , 0 , 0
       0     .08       0   281.2    .045       0   306.2     .08       0
#XS Ineff= 2 , 0
                          346.39          899.12
Permanent Ineff=
       F       F
Bank Sta=281.2,306.2
XS Rating Curve= 0 ,0
Exp/Cntr=0.3,0.1

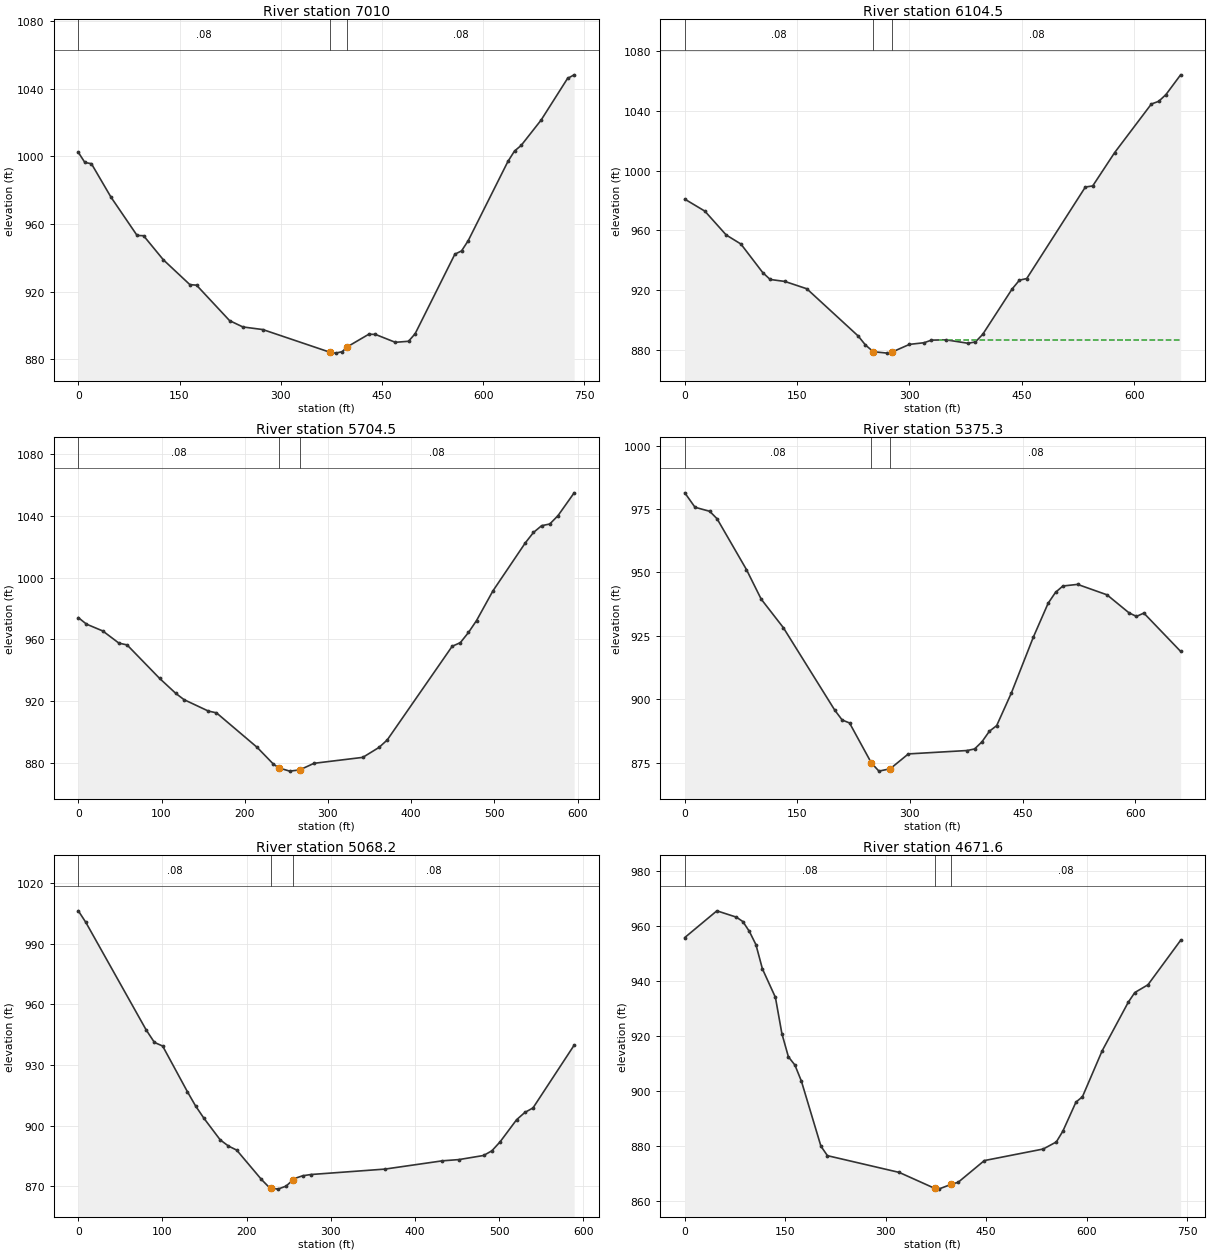
Type RM Length L Ch R = 1 ,7010    ,917.9,905.2,892.5
XS GIS Cut Line= 3
     1671814.395       278718.23     1671808.223      278611.996
     1671771.772      277984.585
#Sta/Elev= 30
       0 1002.38     9.7   996.4    19.4  995.68    48.4  975.89    87.1  953.23
    96.7  953.09     126  938.85   165.3  924.17   175.2  923.84   224.2  902.87
   243.9  899.13   273.4  897.59   373.2  884.14   381.4  883.65   391.2  884.52
   398.2  887.28   430.5  894.82   440.3  894.73   469.8  890.05   489.4  890.66
   499.2  895.13   558.1  942.17     568  944.11   577.8  950.11   636.7     997
   646.5 1003.18   656.3 1006.46   685.8 1021.42   725.1 1046.11   734.9 1048.24
#Mann= 3 , 0 , 0
       0     .08       0   373.2    .045       0   398.2     .08       0
#XS Ineff= 2 , 0
                          434.36           894.7
Permanent Ineff=
       F       F
Bank Sta=373.2,398.2
XS Rating Curve= 0 ,0
Exp/Cntr=0.3,0.1

Type RM Length L Ch R = 1 ,6104.5  ,401.9,399.9,397.9
XS GIS Cut Line= 3
     1672747.689      278359.123     1672730.196      278327.997
     1672423.293      277781.918
#Sta/Elev= 30
       0   980.9    26.8  972.87    55.3  956.91    74.9  950.88   104.2  931.69
     114  927.16   133.6  925.84   162.9  920.94   231.5  889.35   241.2  883.34
   251.7  878.83   270.6  877.88   276.7  878.58     300  883.73   319.6  884.84
   329.3  886.57   348.9  886.77   378.3  884.47   388.1  885.38   397.8  890.44
     437  920.73   446.8  926.66   456.6  927.78   534.9  989.01   544.7  989.73
     574 1012.03     623 1044.52   632.8 1046.33   642.5 1050.85   662.1 1064.06
#Mann= 3 , 0 , 0
       0     .08       0   251.7    .045       0   276.7     .08       0
#XS Ineff= 2 , 0
                          339.18          886.85
Permanent Ineff=
       F       F
Bank Sta=251.7,276.7
XS Rating Curve= 0 ,0
Exp/Cntr=0.3,0.1

Type RM Length L Ch R = 1 ,5704.5  ,328.1,329.2,330.3
XS GIS Cut Line= 3
     1673103.976      278139.336      1673087.81       278114.95
     1672774.727      277642.671
#Sta/Elev= 30
       0  974.09     9.8  969.87    29.3  965.48    48.8  957.58    58.6  956.43
    97.6  934.82   117.2  925.06     127  921.04   156.3  913.64     166   912.5
   214.9  890.18   234.4  879.35   240.9  876.92     254   874.8   265.9  875.57
   283.3  879.86   341.9   883.7   361.4  890.14   371.2  894.93   449.3  955.55
   459.1  957.89   468.9  964.48   478.6  972.21   498.2  991.32   537.3 1022.51
     547 1029.17   556.8 1033.54   566.6 1034.64   576.4 1039.99   595.9  1054.8
#Mann= 3 , 0 , 0
       0     .08       0   240.9    .045       0   265.9     .08       0
Bank Sta=240.9,265.9
XS Rating Curve= 0 ,0
Exp/Cntr=0.3,0.1

Type RM Length L Ch R = 1 ,5375.3  ,303.1,307.1,311.1
XS GIS Cut Line= 3
      1673375.25      277971.991     1673373.278      277968.739
      1673032.64      277407.075
#Sta/Elev= 30
       0  981.37    13.6  975.68    33.2  974.09      43  971.16    82.2  951.12
   101.8   939.5   131.3  928.27   199.9  895.74   209.7   891.9   219.5  890.73
   248.7  874.94   258.7  871.76   273.7  872.69   297.9  878.54   376.4  879.88
   386.2   880.5     396  883.32   405.8  887.44   415.6  889.69   435.2  902.57
   464.6  924.65   484.2   937.9     494  942.17   503.8  944.67   523.4  945.31
   562.6   941.2   592.1  934.06   601.9   932.7   611.7  934.01   660.7  918.92
#Mann= 3 , 0 , 0
       0     .08       0   248.7    .045       0   273.7     .08       0
Bank Sta=248.7,273.7
XS Rating Curve= 0 ,0
Exp/Cntr=0.3,0.1

Type RM Length L Ch R = 1 ,5068.2  ,398.8,396.6,394.4
XS GIS Cut Line= 3
     1673598.521      277817.035     1673567.204       277742.74
     1673369.646      277274.069
#Sta/Elev= 30
       0 1006.23       9 1000.46    80.6  947.31    90.4  941.13   100.2  939.33
   129.5  916.82   139.3  909.71   149.1  903.68   168.6   892.9   178.4  889.85
   188.2  887.83   217.6  873.31   227.3   869.2   229.5  869.05   237.1  868.53
   246.9  870.02   254.5  872.91   256.7  873.75   266.5  875.13   276.2  875.75
   364.3  878.44   432.7  882.54   452.3  883.15   481.6  885.18   491.4  887.49
   501.2  891.93   520.8  902.88   530.6  906.47   540.3  908.71   589.2  939.76
#Mann= 3 , 0 , 0
       0     .08       0   229.5    .045       0   254.5     .08       0
Bank Sta=229.5,254.5
XS Rating Curve= 0 ,0
Exp/Cntr=0.3,0.1

Type RM Length L Ch R = 1 ,4671.6  ,378.1,400.1,422
XS GIS Cut Line= 4
     1673998.486      277714.058     1673994.317      277706.023
     1673882.511      277490.526       1673657.5      277056.839
#Sta/Elev= 30
       0  955.87    47.9   965.6      77   963.3    86.7  961.69    96.4  958.11
   106.2  953.29   115.9  944.46   135.3  934.09     145  920.86   154.7  912.43
   164.4  909.44   174.1  903.57   203.3  879.86     213  876.42   320.2  870.32
     373  864.53   378.9  864.23     398  865.99   408.2  866.72   447.3  874.63
   535.2  878.84   554.8  881.42   564.5  885.33   584.1  895.92   593.8  897.89
   623.2   914.6   662.2   932.3     672  935.84   691.6  938.66   740.4  954.86
#Mann= 3 , 0 , 0
       0     .08       0     373    .045       0     398     .08       0
Bank Sta=373,398
XS Rating Curve= 0 ,0
Exp/Cntr=0.3,0.1

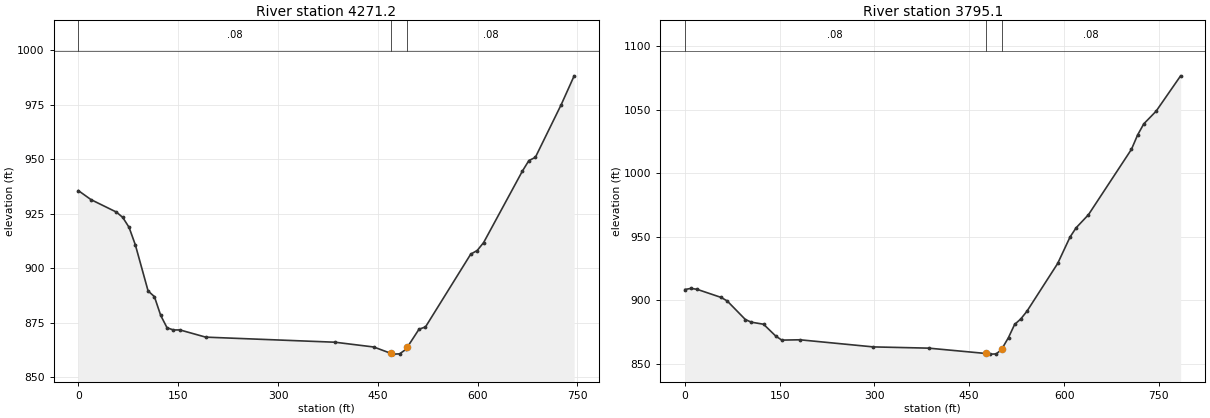
Type RM Length L Ch R = 1 ,4271.2  ,466.5,477.1,487.8
XS GIS Cut Line= 3
     1674038.927      277717.749     1674083.181      277581.912
       1674269.7      277009.401
#Sta/Elev= 30
       0  935.65      19  931.51    57.2  925.79    66.7  923.36    76.2  918.81
    85.7  910.73   104.8  889.65   114.3  887.02   123.8  878.39   133.3  872.74
   142.9  871.74   152.6  871.76   191.4  868.45   385.7  866.12   443.9  863.93
   469.5  861.02   473.1  860.66   482.8  860.78   492.5  862.92   494.5  863.93
   511.9  872.09   521.6  873.12   589.6  906.51   599.3  908.17     609  911.83
   667.3  944.63     677  949.42   686.7  950.89   725.6   975.1     745  988.27
#Mann= 3 , 0 , 0
       0     .08       0   469.5    .045       0   494.5     .08       0
Bank Sta=469.5,494.5
XS Rating Curve= 0 ,0
Exp/Cntr=0.3,0.1

Type RM Length L Ch R = 1 ,3795.1  ,399.3,394.3,389.3
XS GIS Cut Line= 3
     1674193.501      277872.079      1674354.46      277707.683
     1674742.303      277311.559
#Sta/Elev= 30
       0  908.59     9.6  909.45    19.2  908.78    57.5  902.36    67.1  899.58
    95.9  884.93   105.4  882.88   124.6  881.27   143.8  872.01   153.4  868.79
   182.1  869.04   298.2  863.44   385.7  862.47   476.1  858.28     483  857.76
   492.7  857.91   501.1  861.43   512.1  870.83   521.8  881.12   531.6  885.48
   541.3  891.52   589.9  929.09   609.4  949.83   619.1  957.16   638.6  967.44
   706.6 1018.87   716.4 1030.21   726.1 1038.91   745.6 1048.86   784.4 1076.69
#Mann= 3 , 0 , 0
       0     .08       0   476.1    .045       0   501.1     .08       0
Bank Sta=476.1,501.1
XS Rating Curve= 0 ,0
Exp/Cntr=0.3,0.1