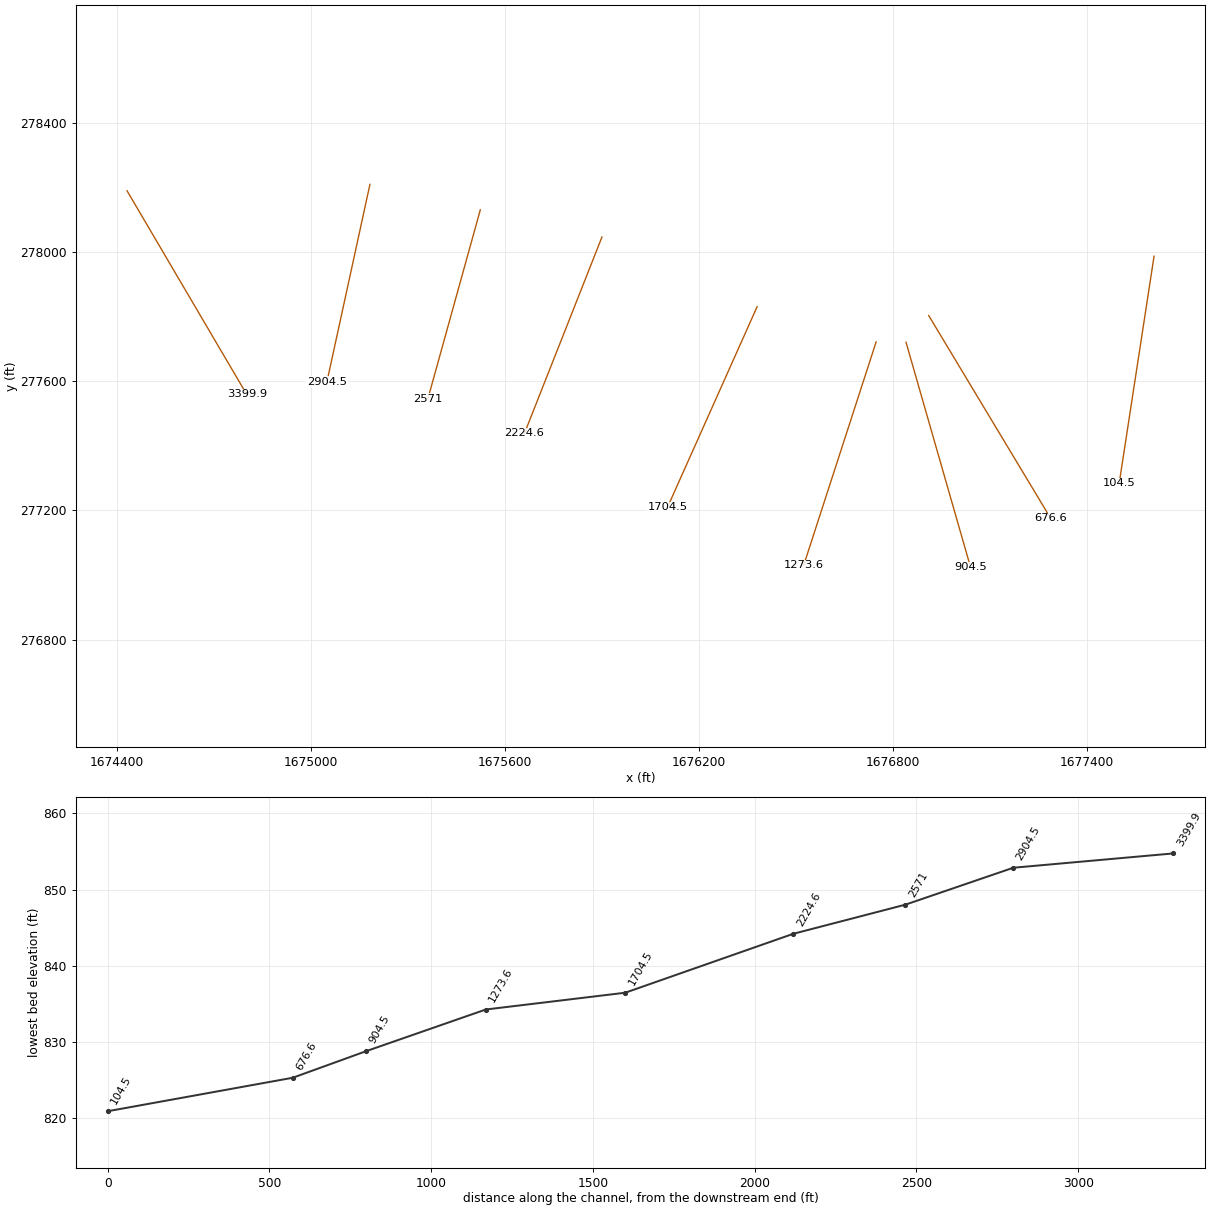
HEC-RAS study PINECRK.prj: PINECRK

--- PINECRK.g01 (geometry) --- (continued)

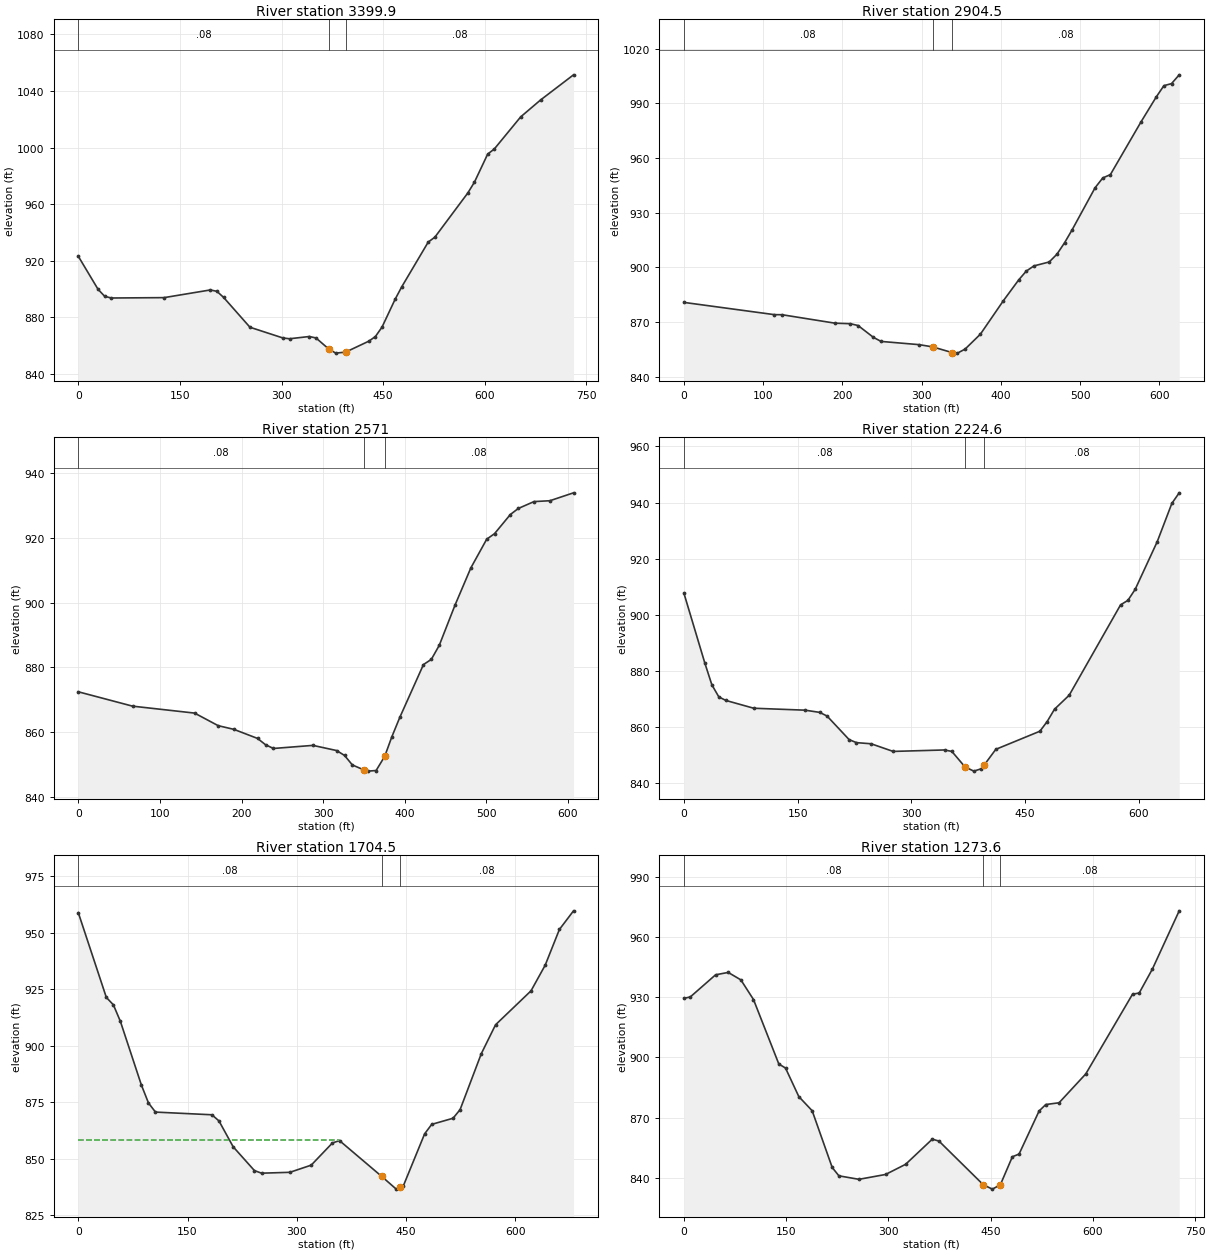
Type RM Length L Ch R = 1 ,3399.9  ,515.8,495.1,474.4
XS GIS Cut Line= 3
     1674431.862      278190.523     1674500.854      278072.903
      1674801.76      277559.904
#Sta/Elev= 30
       0   923.2    29.2  899.83      39  894.88    48.7  893.71   126.6  893.97
   194.9   899.4   204.6  898.43   214.4  894.19   253.4  873.04   302.1  865.45
   311.9   864.9   341.1  866.49   350.9  865.46   369.8  857.63   380.1  854.74
   394.8  855.48   428.9  863.19   438.6  866.47   448.4  873.14   467.8  892.89
   477.6   901.7   516.6  933.25   526.4  936.71   575.1  967.99   584.8  975.59
   604.4  995.46   614.1  999.02   653.1 1021.75   682.4 1033.68   731.1 1051.47
#Mann= 3 , 0 , 0
       0     .08       0   369.8    .045       0   394.8     .08       0
#XS Ineff= 2 , 0
          341.27  865.71
Permanent Ineff=
       F       F
Bank Sta=369.8,394.8
XS Rating Curve= 0 ,0
Exp/Cntr=0.3,0.1

Type RM Length L Ch R = 1 ,2904.5  ,335,333.4,331.9
XS GIS Cut Line= 3
     1675182.963      278210.289     1675150.624      278061.532
     1675050.153      277599.371
#Sta/Elev= 30
       0  880.72   114.2  873.99   123.7  873.96   190.8   869.3   210.1  869.02
   219.8  868.02   239.1  861.54   248.8  859.29     297  857.51   313.9   856.3
   338.9  853.12   345.3  852.86   354.9  855.08   374.2  863.26   403.2  881.64
   422.5  893.04   432.1   897.9   441.8  900.77   461.1  902.93   470.8  907.17
   480.4  913.42   490.1  920.65     519  943.69   528.7  949.08   538.3   950.9
   576.9  979.81   596.2  993.55   605.9  999.77   615.5 1000.89   625.2 1005.72
#Mann= 3 , 0 , 0
       0     .08       0   313.9    .045       0   338.9     .08       0
Bank Sta=313.9,338.9
XS Rating Curve= 0 ,0
Exp/Cntr=0.3,0.1

Type RM Length L Ch R = 1 ,2571    ,349.4,346.5,343.5
XS GIS Cut Line= 3
     1675524.209      278131.417     1675483.653      277984.932
     1675362.304       277546.62
#Sta/Elev= 30
       0  872.49    66.5  868.06   142.5  865.92   171.4  862.04   190.7   860.9
   219.7   858.1   229.4  856.16   239.1  855.01   287.5  855.96   316.5  854.37
   326.2  852.86   335.8  849.93   350.4  848.34   355.2  848.02   364.9  848.21
   375.4  852.55   384.2  858.62   393.9  864.58   422.9  880.88   432.6   882.5
   442.3  886.83   461.6  899.23     481  910.71   500.4  919.55     510  921.26
   529.4  927.17   539.1  929.03   558.4  931.16   577.8  931.42   606.8  933.86
#Mann= 3 , 0 , 0
       0     .08       0   350.4    .045       0   375.4     .08       0
Bank Sta=350.4,375.4
XS Rating Curve= 0 ,0
Exp/Cntr=0.3,0.1

Type RM Length L Ch R = 1 ,2224.6  ,521.1,519.9,518.6
XS GIS Cut Line= 3
     1675900.301      278047.092     1675866.544      277961.396
     1675660.699      277438.847
#Sta/Elev= 30
       0  907.59    27.6  882.68    36.8  874.99      46  870.67    55.3  869.41
    92.1  866.63   159.9  865.94   179.2  865.15   188.9  863.84     218  855.44
   227.7  854.36     247  853.96   276.1  851.23   343.9  851.75   353.6  851.23
     371  845.69   382.6   844.2   392.3  845.03     396  846.27   411.6  851.97
   469.8  858.43   479.4  861.88   489.1  866.28   508.5  871.28   576.3   903.5
     586  905.11   595.6  909.04   624.7  926.04     644  939.69   653.7  943.46
#Mann= 3 , 0 , 0
       0     .08       0     371    .045       0     396     .08       0
Bank Sta=371,396
XS Rating Curve= 0 ,0
Exp/Cntr=0.3,0.1

Type RM Length L Ch R = 1 ,1704.5  ,427.8,430.8,433.9
XS GIS Cut Line= 3
     1676380.053      277831.221     1676321.188       277699.21
     1676103.018      277209.942
#Sta/Elev= 30
       0  958.91    38.5  921.38    48.2  918.09    57.8  910.77    86.7  882.53
    96.4  874.62     106  870.59   183.5   869.4   193.2  866.68   212.7  855.23
   241.9  844.69   251.7  843.53   290.6  843.92   319.9  847.09   349.1  856.93
   358.8  857.95   416.6  842.14   436.7  836.47   441.6  837.22   446.5  837.96
   475.7  860.96   485.4  865.15   514.7  867.86   524.4  871.68   553.6  896.52
   573.1  909.26   621.8  924.29   641.3  935.66   660.8  951.48   680.2  959.73
#Mann= 3 , 0 , 0
       0     .08       0   416.6    .045       0   441.6     .08       0
#XS Ineff= 2 , 0
          357.62  858.21
Permanent Ineff=
       F       F
Bank Sta=416.6,441.6
XS Rating Curve= 0 ,0
Exp/Cntr=0.3,0.1

Type RM Length L Ch R = 1 ,1273.6  ,352.7,369,385.3
XS GIS Cut Line= 3
     1676748.013      277722.099     1676705.171      277589.705
     1676524.281       277030.69
#Sta/Elev= 30
       0  929.47     9.3  930.18    46.4  941.22    64.9   942.4    83.5  938.68
     102  928.88   139.2  896.69     149  894.69   168.5  880.45   188.1  873.39
   217.5  845.08   227.3  840.91   256.7  839.16   295.8  841.58   325.2  846.65
   364.4  859.21   374.2  858.24   439.2  836.46   452.5  834.27   464.2  836.41
   481.9  850.43   491.7  851.76   521.1  873.25   530.9  876.48   550.4  877.36
   589.6  891.76   658.2  931.53     668  932.13   687.5  944.18   726.7  973.14
#Mann= 3 , 0 , 0
       0     .08       0   439.2    .045       0   464.2     .08       0
#XS Ineff= 2 , 0
          366.55  858.57
Permanent Ineff=
       F       F
Bank Sta=439.2,464.2
XS Rating Curve= 0 ,0
Exp/Cntr=0.3,0.1

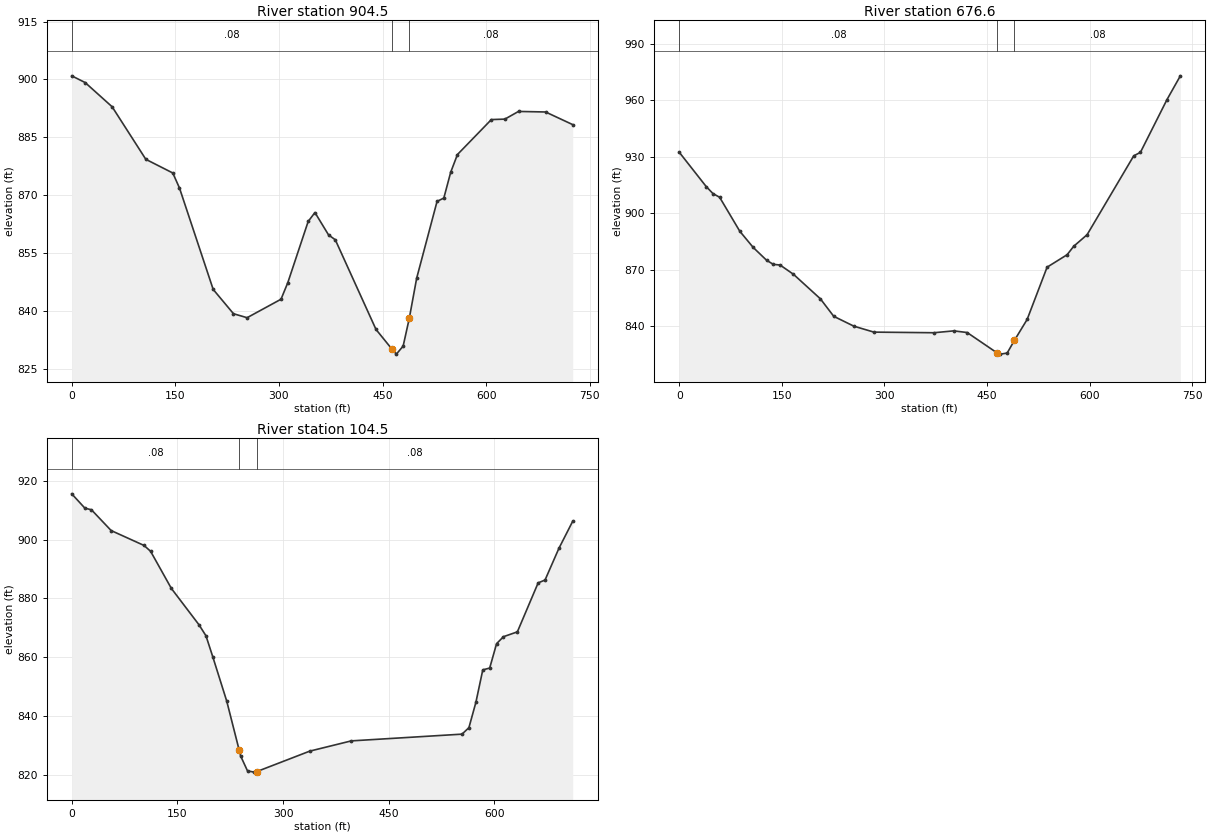
Type RM Length L Ch R = 1 ,904.5   ,220.5,227.8,235.1
XS GIS Cut Line= 3
     1676840.482      277721.111     1676896.834      277524.236
     1677040.084      277023.774
#Sta/Elev= 30
       0  900.95    19.5   899.2    58.5  892.93   107.3  879.31   146.3  875.77
     156  871.88   204.8  845.59   234.2  839.29   253.9  838.26     303  843.05
   312.8  847.33   342.3   863.2   352.1  865.52   371.8  859.72   381.6  858.45
   440.5  835.22   463.7  830.09     470  828.82   479.8   830.9   488.7  838.11
   499.4  848.52   528.9  868.41   538.7  869.27   548.6  875.94   558.4  880.55
   607.5  889.61   627.1  889.73   646.8  891.72     686  891.58   725.3   888.3
#Mann= 3 , 0 , 0
       0     .08       0   463.7    .045       0   488.7     .08       0
Bank Sta=463.7,488.7
XS Rating Curve= 0 ,0
Exp/Cntr=0.3,0.1

Type RM Length L Ch R = 1 ,676.6   ,591.3,572.1,552.9
XS GIS Cut Line= 3
     1676910.631      277803.795     1677041.987      277584.922
     1677287.681      277175.534
#Sta/Elev= 30
       0  932.37    39.3  914.22    49.1  910.53    58.9  908.55    88.4  890.52
     108  881.93   127.6  875.12   137.4  872.96   147.3   872.6   166.9  867.68
   206.2  854.69   225.8  845.38   255.3  840.14   284.5     837   372.2  836.67
   401.4  837.66   420.9  836.78   465.1  825.86   469.6  825.32   479.4  825.88
   490.1  832.67   508.6  843.71   537.8  871.45   567.1  878.07   576.8  882.57
   596.3  888.68   664.5  930.53   674.3  932.39   713.2  960.42   732.7  972.99
#Mann= 3 , 0 , 0
       0     .08       0   465.1    .045       0   490.1     .08       0
Bank Sta=465.1,490.1
XS Rating Curve= 0 ,0
Exp/Cntr=0.3,0.1

Type RM Length L Ch R = 1 ,104.5   ,111.1,104.5,97.9
XS GIS Cut Line= 3
     1677607.384      277987.709     1677590.411       277876.96
     1677499.633      277284.638
#Sta/Elev= 30
       0  915.53    18.7  910.66      28  910.11      56  903.04   102.7  897.98
     112  895.99   141.5  883.36   180.8  870.98   190.6  867.27   200.4  860.04
   220.1  845.05   237.7  828.45   239.8  826.42   249.6  821.33   259.4  820.93
   262.7  821.11     338  828.07   396.9  831.55   554.1  833.84   563.9  836.04
   573.8  844.64   583.6  855.68   593.4  856.31   603.2   864.6     613  866.97
   632.7  868.61   662.2  885.26     672  886.23   691.6  896.96   711.3  906.22
#Mann= 3 , 0 , 0
       0     .08       0   237.7    .045       0   262.7     .08       0
Bank Sta=237.7,262.7
XS Rating Curve= 0 ,0
Exp/Cntr=0.3,0.1

Chan Stop Cuts=-1
Use User Specified Reach Order=0
Composite Channel Slope=5